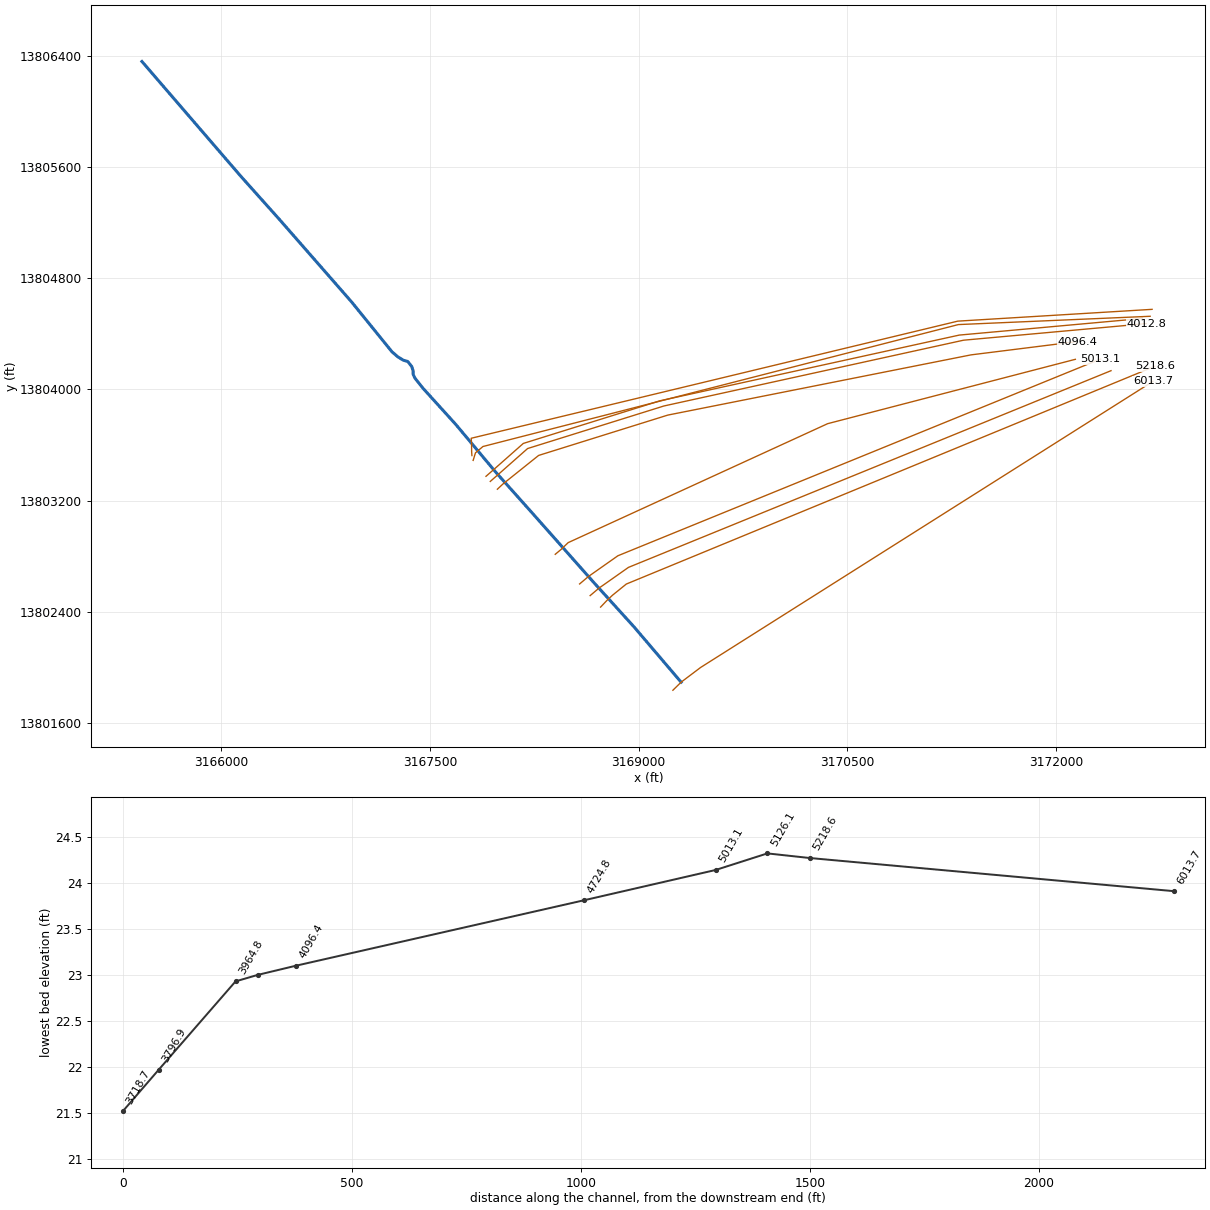
--- C106-08-00.PRJ (project) ---

Proj Title=C106-08-00
Current Plan=p02
Default Exp/Contr=0.3,0.1
English Units
Geom File=g01
Flow File=f01
Flow File=f02
Plan File=p01
Plan File=p02
Y Axis Title=Elevation
X Axis Title(PF)=Main Channel Distance
X Axis Title(XS)=Station
BEGIN DESCRIPTION:
Sims Bayou Watershed
Berry Bayou Tributary 3.31
HCFCD Unit C106-08-00
Flood Hazard Model
10, 2, 1, 0.2% Event
Filename C106-08-00.prj
Prepared by:  Watershed Concepts  Date:
Reviewed by:                      Date:
STATUS FINAL
END DESCRIPTION:
DSS Export Rating Curves= 0
DSS Export Rating Curve Sorted= 0
DSS Export Volume Flow Curves= 0
DXF OffsetX= 0
DXF OffsetY= 0
DXF ScaleX= 1
DXF ScaleY= 10

--- C106-08-00.p02 (plan) ---

Plan Title=Effective Floodway 2015
Program Version=4.10
Short Identifier=RiskMAP FW
Geom File=g01
Flow File=f02
Subcritical Flow
K Sum by GR= 0
Std Step Tol= 0.01
Critical Tol= 0.01
Num of Std Step Trials= 20
Max Error Tol= 0.3
Flow Tol Ratio= 0.001
Split Flow NTrial= 30
Split Flow Tol= 0.02
Split Flow Ratio= 0.02
Log Output Level= 0
Friction Slope Method= 1
Unsteady Friction Slope Method= 2
Unsteady Bridges Friction Slope Method= 1
Parabolic Critical Depth
Global Vel Dist= 0 , 0 , 0
Global Log Level= 0
CheckData=True
Encroach Param=-1 ,0,0, 2
Encroach River=C106-08-00
Encroach Reach=C106-08-00_0009
Encroach Node=6013.7
       1    4920    5140
Encroach Node=5218.6
       1    4944    5160
Encroach Node=5126.1
       1    4918    5185
Encroach Node=5013.1
       1    4918    5185
Encroach Node=4724.8
       1    4950    5170
Encroach Node=4096.4
       1    4945    5170
Encroach Node=4012.8
       1  4938.3    5160
Encroach Node=3964.8
       1  4938.3    5150
Encroach Node=3796.9
       1    4945    5130
Encroach Node=3718.7
       1    4915    5100
Encroach Node=3695.7
       1    4915    5100
Encroach Node=3659.8
       1    4920    5085
Encroach Node=3636.8
       1    4920    5085
Encroach Node=3559.4
       1    4950    5060
Encroach Node=3521.4
       1    4950    5060
Encroach Node=3287.4
       1    4965    5050
Encroach Node=3217.6
       1    4975    5025
Encroach Node=3180.6
       1  4982.1  5017.1
Encroach Node=3074.5
       1 4978.52 5029.39
Encroach Node=3045.5
       1 4978.52 5029.39
Encroach Node=2876.4
       1  4973.3  5017.7
Encroach Node=2350.0
       1  4973.3  5017.8
Encroach Node=1853.8
       1  4973.3  5017.8
Encroach Node=1318.0
       1  4973.3  5017.8
Encroach Node=1182.0
       1  4973.3  5017.8
Encroach Node=1127.7
       1  4973.3  5017.8
Encroach Node=873.9
       1  4973.3  5017.8
BEGIN DESCRIPTION:
FEMA Effective Risk Map Study Floodway May 02, 2019
END DESCRIPTION:
Computation Interval=1HOUR
Output Interval=1HOUR
Run HTab= 0
Run UNet= 0
Run PostProcess= 0
Run WQNet= 0
UNET Theta= 1
UNET Theta Warmup= 1
UNET ZTol= 0.02
UNET ZSATol= 0.1
UNET MxIter= 20
UNET MaxInSteps= 20
UNET DtIC= 0
UNET DtMin= 0
UNET MaxCRTS= 20
UNET WFStab= 2
UNET SFStab= 1
UNET WFX= 1
UNET SFX= 1
UNET DSS MLevel= 4
UNET DZMax Abort= 100
UNET Convert EG Bridges=-1
UNET Use Existing IB Tables=-1
UNET Froude Reduction=False
UNET Froude Limit= 1
UNET Froude Power= 10
UNET Time Slicing=0,0, 5
UNET Junction Losses=0
Instantaneous Interval=1HOUR
Write IC File= 0
IC Time=0,,
Write IC File at Sim End=0
Echo Input=False
Echo Parameters=False
Echo Output=False
Write Detailed= 0
WQ AD Non Conservative
WQ ULTIMATE=-1
WQ Max Comp Step=1HOUR
WQ Output Interval=15MIN
WQ Output Selected Increments= 0
WQ Output face flow=0
WQ Output face velocity=0
WQ Output face area=0
WQ Output face dispersion=0
WQ Output cell volume=0
WQ Output cell surface area=0
WQ Output cell continuity=0
WQ Output cumulative cell continuity=0
WQ Output face conc=0
WQ Output face dconc_dx=0
WQ Output face courant=0
WQ Output face peclet=0
WQ Output face adv mass=0
WQ Output face disp mass=0
WQ Output cell mass=0
WQ Output cell source sink temp=0
WQ Output cell source sink nsm=0
WQ Output MaxMinRange=-1
WQ Daily Max Min Mean=-1
WQ Daily Range=0
WQ Daily Time=0
WQ Create Restart=0
WQ Fixed Restart=0
WQ System Summary=0
WQ Use Fixed Temperature=0
Sorting and Armoring Iterations= 10
XS Update Threshold= 0.02
Hydraulics Update Threshold= 0.02
Energy Slope Method= 1
Volume Change Method= 0
XS Weighting Method= 0
Number of US Weighted Cross Sections= 1
Number of DS Weighted Cross Sections= 1
Upstream XS Weight=0.25
Main XS Weight=0.5
Downstream XS Weight=0.25
Number of DS XS's Weighted with US Boundary= 1
Upstream Boundary Weight= 1
Weight of XSs Associated with US Boundary= 0
Number of US XS's Weighted with DS Boundary= 1
Downstream Boundary Weight= 0.5
Weight of XSs Associated with DS Boundary= 0.5
Sediment Output Level= 4
Mass or Volume Output= 0
Output Increment Type= 1
Profile and TS Output Increment= 10
XS Output Flag= 0
XS Output Increment= 10
Disregard all LS=0
Disregard all Conn=0
Disregard all Breaches=0
Disregard all Pumps=0

--- C106-08-00.p01 (plan) ---

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Plan Title=Effective Multi-Profile 2015
Short Identifier=RiskMAP MP
Geom File=g01
Flow File=f01
Encroach Param=-1 ,0,0, 0
FEMA Effective Risk Map Study Multi-Profile May 02, 2019
UNET ZSATol= 0.05
UNET MaxInSteps= 0

--- C106-08-00.f02 (steady flow) ---

Flow Title=Effective Floodway 2015
Program Version=4.10
Number of Profiles= 2
Profile Names=1PCT_100yr,Floodway
River Rch & RM=C106-08-00,C106-08-00_0009 ,6013.7
    1559    1559
River Rch & RM=C106-08-00,C106-08-00_0009 ,4012.8
    1627    1627
River Rch & RM=C106-08-00,C106-08-00_0009 ,3287.4
    1678    1678
River Rch & RM=C106-08-00,C106-08-00_0009 ,873.9
    1698    1698
Boundary for River Rch & Prof#=C106-08-00,C106-08-00_0009 , 1
Up Type= 0
Dn Type= 3
Dn Slope=0.0015
Boundary for River Rch & Prof#=C106-08-00,C106-08-00_0009 , 2
Up Type= 0
Dn Type= 1
Dn Known WS=24.69
DSS Import GetInterval= 0
DSS Import GetPeak= 0
DSS Import FillOption= 0

--- C106-08-00.f01 (steady flow) ---

Flow Title=Effective Multi-Profile 2015
Program Version=4.10
Number of Profiles= 6
Profile Names=10PCT_10yr,4PCT_25yr,2PCT_50yr,1PCT_100yr,1PCT_Plus,0.2PCT_500yr
River Rch & RM=C106-08-00,C106-08-00_0009 ,6013.7
     914    1135    1337    1559    1871    2189
River Rch & RM=C106-08-00,C106-08-00_0009 ,4012.8
     954    1184    1395    1627    1952    2284
River Rch & RM=C106-08-00,C106-08-00_0009 ,3287.4
     984    1222    1439    1678    2013    2356
River Rch & RM=C106-08-00,C106-08-00_0009 ,873.9
     996    1236    1456    1698    2037    2383
Boundary for River Rch & Prof#=C106-08-00,C106-08-00_0009 , 1
Up Type= 0
Dn Type= 3
Dn Slope=0.0015
Boundary for River Rch & Prof#=C106-08-00,C106-08-00_0009 , 2
Up Type= 0
Dn Type= 3
Dn Slope=0.0015
Boundary for River Rch & Prof#=C106-08-00,C106-08-00_0009 , 3
Up Type= 0
Dn Type= 3
Dn Slope=0.0015
Boundary for River Rch & Prof#=C106-08-00,C106-08-00_0009 , 4
Up Type= 0
Dn Type= 3
Dn Slope=0.0015
DSS Import GetInterval= 0
DSS Import GetPeak= 0
DSS Import FillOption= 0

--- C106-08-00.g01 (geometry) ---

Geom Title=C106-08-00 2015
Program Version=4.10

River Reach=C106-08-00      ,C106-08-00_0009
Reach XY= 20
      3169305.71      13801891.3      3169237.83     13801971.18
      3168967.75       13802289.       3168676.5       13802611.
       3168235.5       13803110.        3167970.       13803408.
        3167686.       13803748.        3167450.       13804009.
        3167392.       13804082.        3167379.       13804110.
        3167379.       13804135.        3167369.       13804166.
      3167340.25       13804202.       3167308.5       13804211.
        3167268.       13804236.      3167226.75       13804272.
       3166937.5       13804630.      3166417.25       13805226.
       3166141.5       13805535.      3165429.75       13806363.

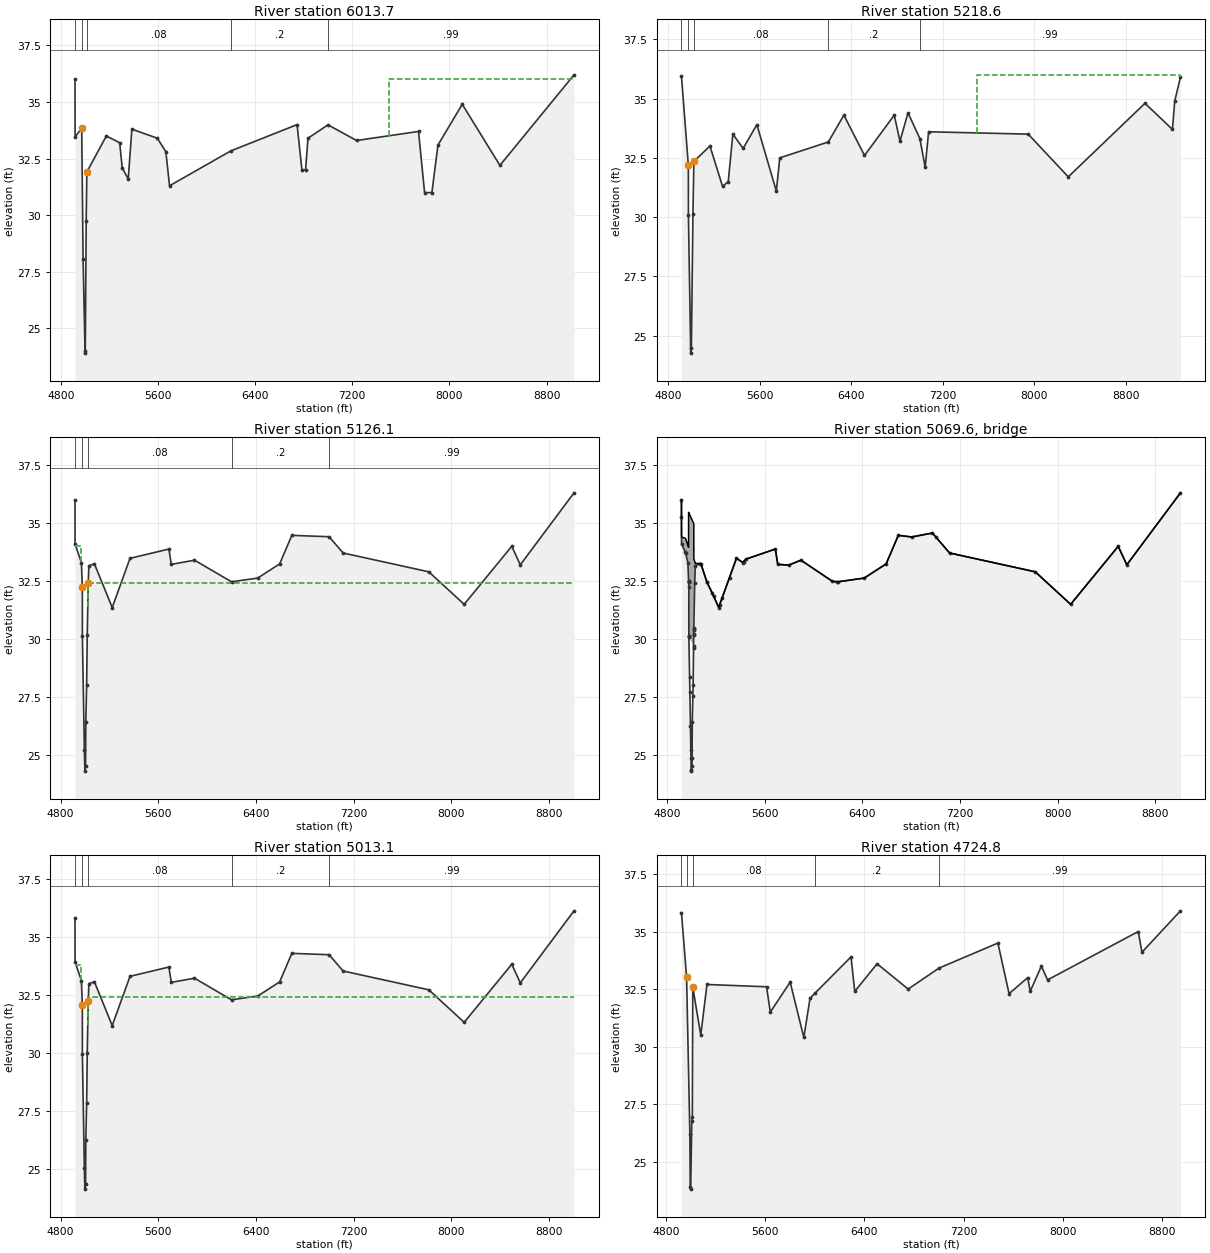
Type RM Length L Ch R = 1 ,6013.7  ,795.3,795.1,633
BEGIN DESCRIPTION:
Cross Section 6013.7
END DESCRIPTION:
XS GIS Cut Line= 4
      3169246.62     13801833.29       3169306.5       13801892.
      3169445.64      13801997.2      3172697.38     13804058.45
#Sta/Elev= 30
  4917.2      36  4918.2   33.46  4972.5   33.84  4983.9   28.06  5000.2   23.91
    5002   23.99  5009.6   29.76  5014.8   31.91  5175.5    33.5  5285.5    33.2
  5305.5    32.1  5355.5    31.6  5385.5    33.8  5595.5    33.4  5665.5    32.8
  5695.5    31.3    6200   32.84  6745.5      34  6785.5      32  6815.5      32
  6835.5    33.4    7000   33.99  7235.5    33.3  7745.5    33.7  7795.5      31
  7855.5      31  7905.5    33.1  8105.5    34.9  8415.5    32.2  9025.5    36.2
#Mann= 5 , 1 , 0
  4917.2     .08       0  4972.5    .015       0  5014.8     .08       0
    6200      .2       0    7000     .99       0
#XS Ineff= 2 , 0
       0                    7500       0      36
Permanent Ineff=
       F       F
Bank Sta=4972.5,5014.8
XS Rating Curve= 0 ,0
Exp/Cntr=0.3,0.1

Type RM Length L Ch R = 1 ,5218.6  ,94,92.5,50
BEGIN DESCRIPTION:
Cross Section 5218.6-Interpolated
END DESCRIPTION:
XS GIS Cut Line= 5
       3168726.9      13802432.3      3168772.83     13802480.78
      3168812.89     13802518.16      3168911.69     13802598.28
      3172710.57     13804166.95
#Sta/Elev= 30
  4917.3   35.95  4977.6   32.18    4978    30.1  4998.2   24.27    5004   24.49
  5017.7   30.13  5025.8   32.35  5166.1      33  5276.1    31.3  5326.1    31.5
  5366.1    33.5  5456.1    32.9  5576.1    33.9  5746.1    31.1  5776.1    32.5
    6200   33.17  6336.1    34.3  6516.1    32.6  6776.1    34.3  6826.1    33.2
  6896.1    34.4    7000   33.31  7046.1    32.1  7076.1    33.6  7946.1    33.5
  8296.1    31.7  8966.1    34.8  9206.1    33.7  9226.1    34.9  9276.1    35.9
#Mann= 5 , 1 , 0
  4917.3     .08       0  4977.6    .015       0  5025.8     .08       0
    6200      .2       0    7000     .99       0
#XS Ineff= 2 , 0
       0                    7500       0      36
Permanent Ineff=
       F       F
Bank Sta=4977.6,5025.8
XS Rating Curve= 0 ,0
Exp/Cntr=0.5,0.3

Type RM Length L Ch R = 1 ,5126.1  ,113,113,113
BEGIN DESCRIPTION:
Upstream Section of Bridge/Culvert/Weir
END DESCRIPTION:
XS GIS Cut Line= 4
      3168651.79      13802515.1      3168715.87     13802569.35
      3168927.17     13802718.33       3172396.1      13804135.4
#Sta/Elev= 30
  4917.3      36  4917.8    34.1  4969.8    33.3  4977.6   32.23  4977.8   30.15
  4994.1   25.21  4998.2   24.32    5004   24.54  5005.9   26.43  5012.9   28.03
  5017.7   30.18  5025.8    32.4  5031.1   33.16    5076   33.25  5222.4   31.36
  5368.2   33.48  5686.7   33.88  5706.7   33.22  5896.7    33.4    6200   32.47
  6414.6   32.63  6594.6   33.24  6694.6   34.47    7000   34.41  7114.6   33.71
    7817    32.9    8107    31.5    8497      34    8567    33.2    9007    36.3
#Mann= 5 ,-1 , 0
  4917.3     .08       0  4977.6    .015       0  5025.8     .08       0
    6200      .2       0    7000     .99       0
#XS Ineff= 2 , 0
       0  4967.5      34  5022.1       0    32.4
Permanent Ineff=
       F       F
Bank Sta=4977.6,5025.8
XS Rating Curve= 0 ,0
Exp/Cntr=0.5,0.3

Type RM Length L Ch R = 3 ,5069.6  ,,,
BEGIN DESCRIPTION:
EDGEBROOK DRIVE
Structure ID: C68-7
END DESCRIPTION:
Bridge Culvert--1,0,-1,-1, 0
Deck Dist Width WeirC Skew NumUp NumDn MinLoCord MaxHiCord MaxSubmerge Is_Ogee
10,93,3,0, 39, 39, , , 0.95, 0, 1,1,,
  4917.3  4917.5  4917.8  4950.5  4969.8 4975.59  4975.7  4977.6  4977.8 4977.91
  5016.6  5017.7  5018.6 5018.71  5025.8  5031.1    5076  5125.4  5222.4  5368.2
  5418.2  5448.2  5686.7  5706.7  5796.7  5896.7  6154.6    6200  6414.6  6594.6
  6694.6  6804.6  6974.6  7114.6    7817    8107    8497    8567    9007
      36   35.25    34.4   34.34   34.05   33.96   35.46   35.44   35.44   35.44
   34.99   34.98   34.96   33.46   33.34   33.26   33.26   32.47   31.37   33.49
   33.31   33.45   33.88   33.22   33.19    33.4   32.49   32.47   32.63   33.24
   34.47    34.4   34.57   33.71    32.9    31.5      34    33.2    36.3
      36   35.24    34.1    33.7    33.3   32.51   32.49   32.23   30.15   30.12
   29.69   30.18   30.43   30.46    32.4   33.16   33.25   32.46   31.36   33.48
    33.3   33.45   33.88   33.22   33.19    33.4   32.49   32.47   32.63   33.24
   34.47    34.4   34.57   33.71    32.9    31.5      34    33.2    36.3
  4917.3  4917.5  4917.8  4950.5  4969.8 4975.59  4975.7  4977.6  4977.8 4977.91
  5016.6  5017.7  5018.6 5018.71  5025.8  5031.1    5076  5125.4  5222.4  5368.2
  5418.2  5448.2  5686.7  5706.7  5796.7  5896.7  6154.6    6200  6414.6  6594.6
  6694.6  6804.6  6974.6  7114.6    7817    8107    8497    8567    9007
      36   35.25    34.4   34.34   34.05   33.96   35.46   35.44   35.44   35.44
   34.99   34.98   34.96   33.46   33.34   33.26   33.26   32.47   31.37   33.49
   33.31   33.45   33.88   33.22   33.19    33.4   32.49   32.47   32.63   33.24
   34.47    34.4   34.57   33.71    32.9    31.5      34    33.2    36.3
   35.83   35.07   33.93   33.53   33.13   32.34   32.32   32.06   29.98   29.95
   29.52   30.01   30.26   30.29   32.23   32.99   33.08   32.29   31.19   33.31
   33.13   33.28   33.71   33.05   33.02   33.23   32.32    32.3   32.46   33.07
    34.3   34.23    34.4   33.54   32.73   31.33   33.83   33.03   36.13
Abutment Skew #Up #Dn= , 2 , 2
  4977.8  4984.1
   30.14   28.37
  4977.8  4984.1
   29.97    28.2
Abutment Skew #Up #Dn= , 2 , 2
  5010.9 5016.69
   27.57    29.7
  5010.9 5016.69
    27.4   29.53
BR Coef= 1 , 1 , 0 ,1.25, 0 ,,,0.8,0,2,0,
WSPro=,,,, 1 ,,,, 0 ,,,, 0 ,,,,-1 ,-1 ,-1 , 0 , 0 , 0 , 0 , 0
BR U #Sta/Elev= 68
  4917.3      36  4917.5   35.24  4917.8    34.1  4948.2   33.75  4950.5    33.7
  4969.8    33.3 4975.59   32.51  4975.7   32.49 4975.81   32.48  4976.1   32.44
  4977.6   32.23  4977.8   30.15 4977.91   30.12    4978   30.09  4984.1   28.37
  4986.4   27.72  4991.1   26.25  4994.1   25.21  4995.5    24.9  4997.2   24.38
  4998.2   24.32    5004   24.54  5004.5    24.9  5005.9   26.43  5010.9   27.57
  5012.9   28.03 5016.49   29.64  5016.6   29.69  5017.7   30.18  5017.9   30.23
 5018.49    30.4  5018.6   30.43 5018.71   30.46  5025.8    32.4  5031.1   33.16
  5068.8   33.24    5076   33.25  5124.9   32.47  5125.4   32.46  5171.4   31.98
  5182.3   31.85  5222.4   31.36  5231.2   31.49  5251.3   31.78  5311.3   32.65
  5368.2   33.48  5418.2    33.3    5426   33.34  5448.2   33.45  5686.7   33.88
  5706.7   33.22  5796.7   33.19  5896.7    33.4  6154.6   32.49  6194.6   32.47
    6200   32.47  6414.6   32.63  6594.6   33.24  6694.6   34.47  6804.6    34.4
  6974.6   34.57    7000   34.41  7114.6   33.71    7817    32.9    8107    31.5
    8497      34    8567    33.2    9007    36.3
BR U #Mann= 5
  4917.3     .08  4977.6    .015  5025.8     .08    6200      .2    7000     .99
BR U Banks=4977.6,5025.8
BR D #Sta/Elev= 68
  4917.3   35.83  4917.5   35.07  4917.8   33.93  4948.2   33.58  4950.5   33.53
  4969.8   33.13 4975.59   32.34  4975.7   32.32 4975.81   32.31  4976.1   32.27
  4977.6   32.06  4977.8   29.98 4977.91   29.95    4978   29.92  4984.1    28.2
  4986.4   27.55  4991.1   26.08  4994.1   25.04  4995.5   24.73  4997.2   24.21
  4998.2   24.15    5004   24.37  5004.5   24.73  5005.9   26.26  5010.9    27.4
  5012.9   27.86 5016.49   29.47  5016.6   29.52  5017.7   30.01  5017.9   30.06
 5018.49   30.23  5018.6   30.26 5018.71   30.29  5025.8   32.23  5031.1   32.99
  5068.8   33.07    5076   33.08  5124.9    32.3  5125.4   32.29  5171.4   31.81
  5182.3   31.68  5222.4   31.19  5231.2   31.32  5251.3   31.61  5311.3   32.48
  5368.2   33.31  5418.2   33.13    5426   33.17  5448.2   33.28  5686.7   33.71
  5706.7   33.05  5796.7   33.02  5896.7   33.23  6154.6   32.32  6194.6    32.3
    6200    32.3  6414.6   32.46  6594.6   33.07  6694.6    34.3  6804.6   34.23
  6974.6    34.4    7000   34.24  7114.6   33.54    7817   32.73    8107   31.33
    8497   33.83    8567   33.03    9007   36.13
BR D #Mann= 5
  4917.3     .08  4977.6    .015  5025.8     .08    6200      .2    7000     .99
BR D Banks=4977.6,5025.8
BC Design=,, 0 ,, 0 ,,,,,,
BC HTab HWMax=36.3
BC Use User HTab Curves=0
BC User HTab FreeFlow(D)= 0

Type RM Length L Ch R = 1 ,5013.1  ,289.2,288.3,262.9
BEGIN DESCRIPTION:
Downstream Section of Bridge/Culvert/Weir
END DESCRIPTION:
XS GIS Cut Line= 4
      3168575.99      13802598.9      3168640.07     13802653.15
      3168851.37     13802802.13      3172320.29      13804219.2
#Sta/Elev= 30
  4917.3   35.82  4917.8   33.92  4969.8   33.12  4977.6   32.05  4977.8   29.97
  4994.1   25.03  4998.2   24.14    5004   24.36  5005.9   26.25  5012.9   27.85
  5017.7      30  5025.8   32.22  5031.1   32.98    5076   33.07  5222.4   31.18
  5368.2    33.3  5686.7    33.7  5706.7   33.04  5896.7   33.22    6200   32.29
  6414.6   32.45  6594.6   33.06  6694.6   34.29    7000   34.23  7114.6   33.53
    7817   32.72    8107   31.32    8497   33.82    8567   33.02    9007   36.12
#Mann= 5 ,-1 , 0
  4917.3     .08       0  4977.6    .015       0  5025.8     .08       0
    6200      .2       0    7000     .99       0
#XS Ineff= 2 , 0
       0  4967.5    33.8  5022.1       0    32.4
Permanent Ineff=
       F       F
Bank Sta=4977.6,5025.8
XS Rating Curve= 0 ,0
Exp/Cntr=0.5,0.3

Type RM Length L Ch R = 1 ,4724.8  ,629.8,628.4,559.9
BEGIN DESCRIPTION:
Cross Section 4724.8-Interpolated
END DESCRIPTION:
XS GIS Cut Line= 5
      3168400.86     13802812.56       3168441.7     13802846.63
      3168493.77      13802896.6      3170359.07     13803753.67
      3172139.66     13804217.34
#Sta/Elev= 30
  4926.9   35.82  4968.3   33.01  4994.6   26.21  4997.7   23.89    5001   23.81
  5010.3   26.77  5014.5   26.93    5018   32.59  5082.3    30.5  5132.3    32.7
  5612.3    32.6  5642.3    31.5  5802.3    32.8  5912.3    30.4  5962.3    32.1
    6000   32.31  6292.3    33.9  6322.3    32.4  6502.3    33.6  6752.3    32.5
    7000   33.41    7475    34.5    7565    32.3    7715      33    7735    32.4
    7825    33.5    7875    32.9    8605      35    8635    34.1    8945    35.9
#Mann= 5 , 1 , 0
  4926.9     .08       0  4968.3    .015       0    5018     .08       0
    6000      .2       0    7000     .99       0
#XS Ineff= 2 , 0
       0                    7475       0    34.5
Permanent Ineff=
       F       F
Bank Sta=4968.3,5018
XS Rating Curve= 0 ,0
Exp/Cntr=0.3,0.1

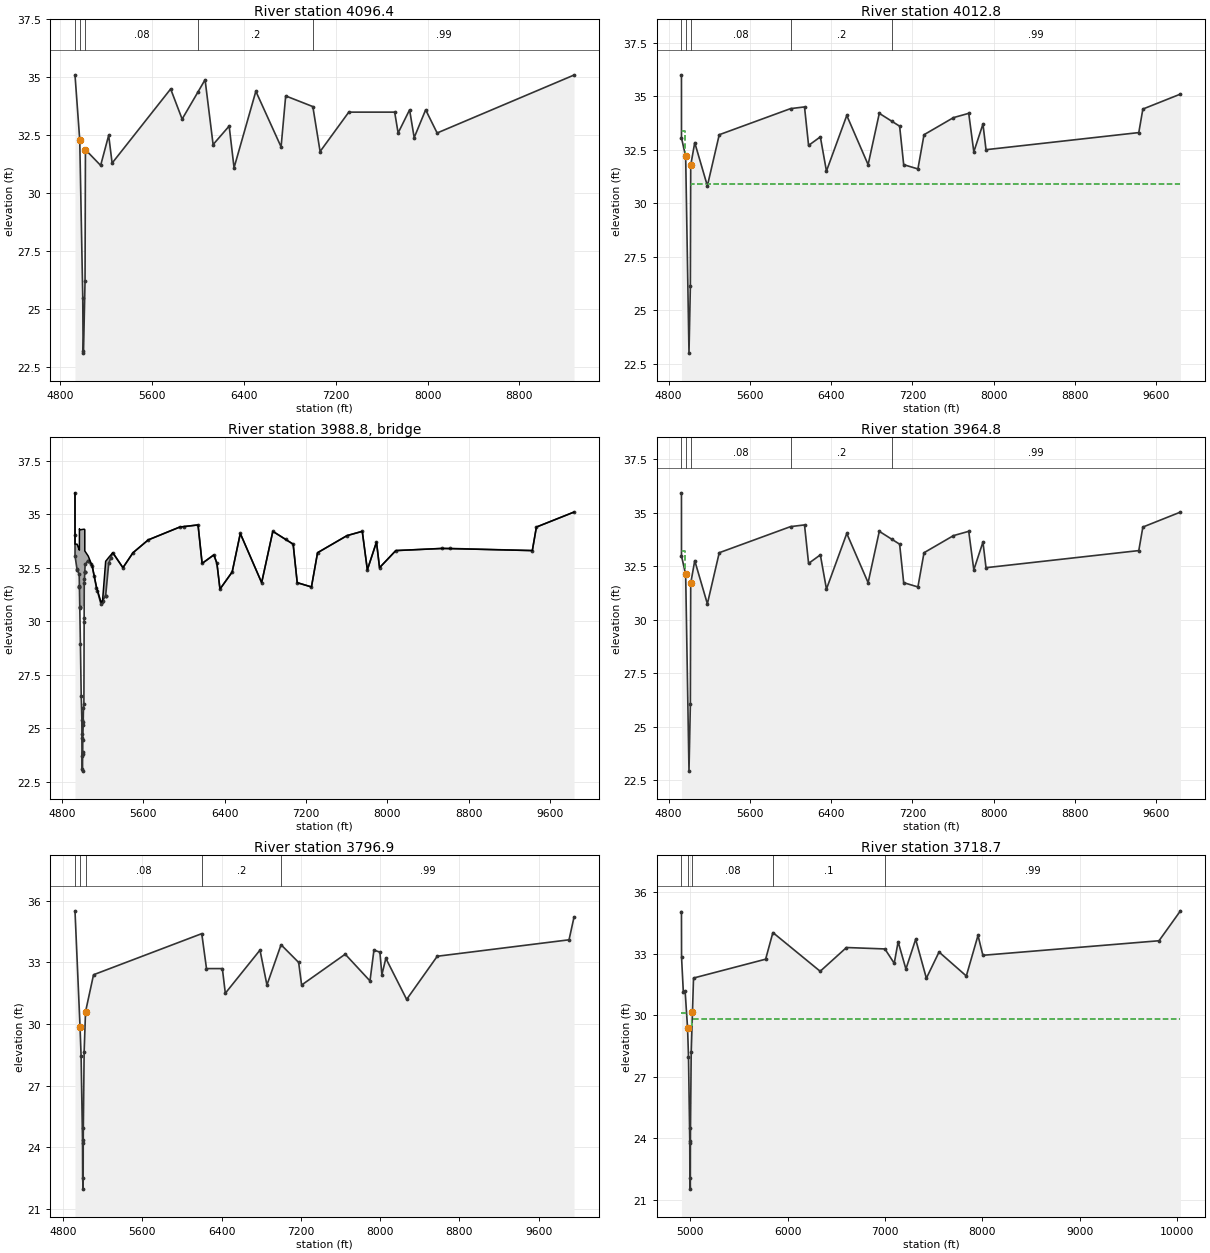
Type RM Length L Ch R = 1 ,4096.4  ,75.1,83.6,62.8
BEGIN DESCRIPTION:
Cross Section 4096.4-Interpolated
END DESCRIPTION:
XS GIS Cut Line= 6
      3167984.83     13803281.53      3168025.11     13803319.29
      3168281.47     13803524.92      3169209.66     13803815.41
      3171389.87     13804249.35      3172153.88     13804345.16
#Sta/Elev= 30
  4926.9   35.11  4968.3    32.3  4994.6    25.5  4997.7   23.18    5001    23.1
  5014.5   26.22    5018   31.88  5150.5    31.2  5220.5    32.5  5250.5    31.3
  5760.7    34.5  5860.7    33.2    6000   34.38  6060.7    34.9  6130.7    32.1
  6270.7    32.9  6313.3    31.1  6503.3    34.4  6723.3      32  6763.3    34.2
    7000   33.74  7063.3    31.8  7313.3    33.5  7713.3    33.5  7743.3    32.6
  7843.3    33.6  7883.3    32.4  7983.3    33.6  8083.3    32.6  9276.3    35.1
#Mann= 5 , 1 , 0
  4926.9     .08       0  4968.3    .015       0    5018     .08       0
    6000      .2       0    7000     .99       0
#XS Ineff= 2 , 0
       0                  6503.3       0    34.4
Permanent Ineff=
       F       F
Bank Sta=4968.3,5018
XS Rating Curve= 0 ,0
Exp/Cntr=0.5,0.3

Type RM Length L Ch R = 1 ,4012.8  ,48,48,48
BEGIN DESCRIPTION:
Upstream Section of Bridge/Culvert/Weir
END DESCRIPTION:
XS GIS Cut Line= 6
       3167933.8      13803337.6      3167987.81     13803384.82
      3168202.06     13803574.49       3169182.3     13803881.15
      3171335.78       13804355.      3172650.28     13804474.57
#Sta/Elev= 30
  4926.9   36.01  4927.2   33.06  4968.3    32.2    5001      23  5014.5   26.12
    5018   31.78  5057.6   32.84  5181.9   30.82  5298.7   33.21    6000   34.43
  6137.7   34.51  6177.7   32.71  6293.5   33.11  6353.5   31.51  6553.5   34.11
  6763.5   31.81  6873.5   34.21    7000   33.83  7073.5   33.61  7113.5   31.81
  7253.5   31.61  7313.5   33.21  7603.5   34.01  7753.5   34.21  7803.5   32.41
  7893.5   33.71  7923.5   32.51  9426.8   33.31  9466.8   34.41  9836.8   35.11
#Mann= 5 ,-1 , 0
  4926.9     .08       0  4968.3    .015       0    5018     .08       0
    6000      .2       0    7000     .99       0
#XS Ineff= 2 , 0
       0  4963.8    33.4  5017.4       0    30.9
Permanent Ineff=
       F       F
Bank Sta=4968.3,5018
XS Rating Curve= 0 ,0
Exp/Cntr=0.5,0.3

Type RM Length L Ch R = 3 ,3988.8  ,,,
BEGIN DESCRIPTION:
ACCESS ROAD 3
Structure ID: C68-6
END DESCRIPTION:
Bridge Culvert--1,0,-1,-1, 0
Deck Dist Width WeirC Skew NumUp NumDn MinLoCord MaxHiCord MaxSubmerge Is_Ogee
10,28,2.6,0, 50, 50, , , 0.95, 0, 1,1,,
  4926.9  4927.1  4927.2  4947.1  4968.3 4970.29  4970.4 4973.91 5016.89    5017
    5018  5023.4 5023.51  5026.8  5057.6  5096.2  5138.1  5181.9  5191.1  5198.7
  5228.7  5258.9  5298.7  5398.7  5497.7  5647.7  5957.7  6137.7  6177.7  6293.5
  6323.5  6353.5  6473.5  6553.5  6763.5  6873.5  7073.5  7113.5  7253.5  7313.5
  7603.5  7753.5  7803.5  7893.5  7923.5  8083.5  8536.8  9426.8  9466.8  9836.8
      36   34.04    33.6    33.6   33.35   33.32   34.32   34.27    34.3    34.3
    34.3   34.28   33.28   33.26   33.04   32.58   31.61    30.9    30.9      31
    32.8   32.98    33.2    32.5    33.2    33.8    34.4    34.5    32.7    33.1
    32.7    31.5    32.3    34.1    31.8    34.2    33.6    31.8    31.6    33.2
      34    34.2    32.4    33.7    32.5    33.3    33.4    33.3    34.4    35.1
      36   34.03   33.05   32.42   32.19   31.64   31.61   30.65   30.71   30.15
   31.77   32.31   32.32   32.65   32.83   32.57   31.56   30.81   30.89   30.95
    31.2    32.7    33.2    32.5    33.2    33.8    34.4    34.5    32.7    33.1
    32.7    31.5    32.3    34.1    31.8    34.2    33.6    31.8    31.6    33.2
      34    34.2    32.4    33.7    32.5    33.3    33.4    33.3    34.4    35.1
  4926.9  4927.1  4927.2  4947.1  4968.3 4970.29  4970.4 4973.91 5016.89    5017
    5018  5023.4 5023.51  5026.8  5057.6  5096.2  5138.1  5181.9  5191.1  5198.7
  5228.7  5258.9  5298.7  5398.7  5497.7  5647.7  5957.7  6137.7  6177.7  6293.5
  6323.5  6353.5  6473.5  6553.5  6763.5  6873.5  7073.5  7113.5  7253.5  7313.5
  7603.5  7753.5  7803.5  7893.5  7923.5  8083.5  8536.8  9426.8  9466.8  9836.8
      36   34.04    33.6    33.6   33.35   33.32   34.32   34.27    34.3    34.3
    34.3   34.28   33.28   33.26   33.04   32.58   31.61    30.9    30.9      31
    32.8   32.98    33.2    32.5    33.2    33.8    34.4    34.5    32.7    33.1
    32.7    31.5    32.3    34.1    31.8    34.2    33.6    31.8    31.6    33.2
      34    34.2    32.4    33.7    32.5    33.3    33.4    33.3    34.4    35.1
      36   34.03   33.05   32.42   32.19   31.64   31.61   30.65   30.71   30.15
   31.77   32.31   32.32   32.65   32.83   32.57   31.56   30.81   30.89   30.95
    31.2    32.7    33.2    32.5    33.2    33.8    34.4    34.5    32.7    33.1
    32.7    31.5    32.3    34.1    31.8    34.2    33.6    31.8    31.6    33.2
      34    34.2    32.4    33.7    32.5    33.3    33.4    33.3    34.4    35.1
Abutment Skew #Up #Dn= , 2 , 2
  4973.8  4995.1
   30.68   24.55
  4973.8  4995.1
   30.68   24.55
Abutment Skew #Up #Dn= , 2 , 2
  5007.6 5017.09
   25.28   30.71
  5007.6 5017.09
   25.28   30.71
BR Coef= 1 , 1 , 0 ,1.25, 0 ,,,0.8,0,2,0,
WSPro=,,,, 1 ,,,, 0 ,,,, 0 ,,,,-1 ,-1 ,-1 , 0 , 0 , 0 , 0 , 0
BR U #Sta/Elev= 80
  4926.9      36  4927.1   34.03  4927.2   33.05  4947.1   32.42  4950.5   32.38
  4968.3   32.19 4970.29   31.64  4970.4   31.61 4970.51   31.58  4973.8   30.68
 4973.91   30.65    4974   30.63  4980.2   28.93  4988.1   26.52  4994.6   25.39
    4995   24.72  4995.1   24.55  4997.1   23.71  4997.7   23.07    5001   22.99
  5001.8   23.77  5002.8   23.89  5003.6   24.45    5007   25.13  5007.6   25.28
  5010.3   25.95  5014.5   26.11 5016.89   29.97    5017   30.15    5018   31.77
    5020   31.97 5023.29    32.3  5023.4   32.31 5023.51   32.32  5026.8   32.65
  5051.7    32.8  5057.6   32.83  5080.1   32.68  5096.2   32.57  5115.2   32.11
  5138.1   31.56  5147.6    31.4  5181.9   30.81  5191.1   30.89  5198.7   30.95
  5228.7    31.2  5228.9    31.2  5258.9    32.7  5278.9   32.95  5298.7    33.2
  5398.7    32.5  5497.7    33.2  5647.7    33.8  5957.7    34.4    6000   34.42
  6137.7    34.5  6177.7    32.7  6293.5    33.1  6323.5    32.7  6353.5    31.5
  6473.5    32.3  6553.5    34.1  6763.5    31.8  6873.5    34.2    7000   33.82
  7073.5    33.6  7113.5    31.8  7253.5    31.6  7313.5    33.2  7603.5      34
  7753.5    34.2  7803.5    32.4  7893.5    33.7  7923.5    32.5  8083.5    33.3
  8536.8    33.4  8616.8    33.4  9426.8    33.3  9466.8    34.4  9836.8    35.1
BR U #Mann= 5
  4926.9     .08  4968.3    .015    5018     .08    6000      .2    7000     .99
BR U Banks=4968.3,5018
BR D #Sta/Elev= 80
  4926.9      36  4927.1   34.03  4927.2   33.05  4947.1   32.42  4950.5   32.38
  4968.3   32.19 4970.29   31.64  4970.4   31.61 4970.51   31.58  4973.8   30.68
 4973.91   30.65    4974   30.63  4980.2   28.93  4988.1   26.52  4994.6   25.39
    4995   24.72  4995.1   24.55  4997.1   23.71  4997.7   23.07    5001   22.99
  5001.8   23.77  5002.8   23.89  5003.6   24.45    5007   25.13  5007.6   25.28
  5010.3   25.95  5014.5   26.11 5016.89   29.97    5017   30.15    5018   31.77
    5020   31.97 5023.29    32.3  5023.4   32.31 5023.51   32.32  5026.8   32.65
  5051.7    32.8  5057.6   32.83  5080.1   32.68  5096.2   32.57  5115.2   32.11
  5138.1   31.56  5147.6    31.4  5181.9   30.81  5191.1   30.89  5198.7   30.95
  5228.7    31.2  5228.9    31.2  5258.9    32.7  5278.9   32.95  5298.7    33.2
  5398.7    32.5  5497.7    33.2  5647.7    33.8  5957.7    34.4    6000   34.42
  6137.7    34.5  6177.7    32.7  6293.5    33.1  6323.5    32.7  6353.5    31.5
  6473.5    32.3  6553.5    34.1  6763.5    31.8  6873.5    34.2    7000   33.82
  7073.5    33.6  7113.5    31.8  7253.5    31.6  7313.5    33.2  7603.5      34
  7753.5    34.2  7803.5    32.4  7893.5    33.7  7923.5    32.5  8083.5    33.3
  8536.8    33.4  8616.8    33.4  9426.8    33.3  9466.8    34.4  9836.8    35.1
BR D #Mann= 5
  4926.9     .08  4968.3    .015    5018     .08    6000      .2    7000     .99
BR D Banks=4968.3,5018
BC Design=,, 0 ,, 0 ,,,,,,
BC HTab HWMax=36.01
BC Use User HTab Curves=0
BC User HTab FreeFlow(D)= 0

Type RM Length L Ch R = 1 ,3964.8  ,168.2,167.9,167.4
BEGIN DESCRIPTION:
Downstream Section of Bridge/Culvert/Weir
END DESCRIPTION:
XS GIS Cut Line= 6
      3167903.02     13803374.44      3167957.03     13803421.66
      3168171.28     13803611.33      3169151.52     13803917.99
        3171305.     13804391.84      3172619.51     13804511.41
#Sta/Elev= 30
  4926.9   35.94  4927.2   32.99  4968.3   32.13    5001   22.93  5014.5   26.05
    5018   31.71  5057.6   32.77  5181.9   30.75  5298.7   33.14    6000   34.36
  6137.7   34.44  6177.7   32.64  6293.5   33.04  6353.5   31.44  6553.5   34.04
  6763.5   31.74  6873.5   34.14    7000   33.76  7073.5   33.54  7113.5   31.74
  7253.5   31.54  7313.5   33.14  7603.5   33.94  7753.5   34.14  7803.5   32.34
  7893.5   33.64  7923.5   32.44  9426.8   33.24  9466.8   34.34  9836.8   35.04
#Mann= 5 ,-1 , 0
  4926.9     .08       0  4968.3    .015       0    5018     .08       0
    6000      .2       0    7000     .99       0
#XS Ineff= 2 , 0
       0  4963.8    33.2  5017.4       0    30.7
Permanent Ineff=
       F       F
Bank Sta=4968.3,5018
XS Rating Curve= 0 ,0
Exp/Cntr=0.5,0.3

Type RM Length L Ch R = 1 ,3796.9  ,78.1,78.2,127.9
BEGIN DESCRIPTION:
Cross Section 3796.9-Interpolated
END DESCRIPTION:
XS GIS Cut Line= 5
      3167810.71     13803489.03       3167827.5     13803543.61
      3167880.91     13803589.01       3171298.7     13804467.55
      3172677.34     13804527.33
#Sta/Elev= 30
 4920.46   35.51 4971.56   29.84 4982.16   28.43 4996.36   24.34 4997.76    22.5
 5002.76   21.97 5003.66   24.21 5004.66   24.95 5012.86   28.65 5026.86    30.6
  5107.6    32.4  6199.9    34.4  6247.6    32.7  6407.6    32.7  6437.6    31.5
  6787.6    33.6  6857.6    31.9    7000   33.86  7177.6      33  7207.6    31.9
  7647.6    33.4  7897.6    32.1  7937.6    33.6  7997.6    33.5  8017.6    32.4
  8057.6    33.2  8267.6    31.2  8576.5    33.3  9906.5    34.1  9956.5    35.2
#Mann= 5 , 1 , 0
 4920.46     .08       0 4971.56    .015       0 5026.86     .08       0
  6199.9      .2       0    7000     .99       0
Bank Sta=4971.56,5026.86
XS Rating Curve= 0 ,0
Exp/Cntr=0.5,0.3

Type RM Length L Ch R = 1 ,3718.7  ,23,23,23
BEGIN DESCRIPTION:
Upstream Section of Bridge/Culvert/Weir
END DESCRIPTION:
XS GIS Cut Line= 6
      3167801.77     13803524.06      3167799.89     13803552.11
      3167799.19     13803613.91      3167796.67     13803648.57
      3171294.72     13804492.34      3172691.29     13804577.31
#Sta/Elev= 30
  4911.5   35.06  4912.5   32.83 4930.71   31.14 4949.09   31.18 4974.12   29.39
 4983.77   27.98 4996.69   23.89 4997.96   22.05 5002.51   21.52 5003.33   23.76
 5004.24    24.5  5011.7    28.2 5024.44   30.15 5035.36   31.82  5775.5   32.74
    5850   34.04  6335.5   32.15  6605.5   33.31    7000   33.24  7095.5   32.54
  7135.5   33.59  7215.5   32.26  7315.5   33.71  7425.5   31.81  7555.5   33.09
  7835.5   31.92  7955.5    33.9  8005.5   32.93  9813.7   33.64 10033.7    35.1
#Mann= 5 , 1 , 0
  4911.5     .08       0 4974.12    .015       0 5024.44     .08       0
    5850      .1       0    7000     .99       0
#XS Ineff= 2 , 0
       0  4965.7    30.1    5020       0    29.8
Permanent Ineff=
       F       F
Bank Sta=4974.12,5024.44
XS Rating Curve= 0 ,0
Exp/Cntr=0.5,0.3