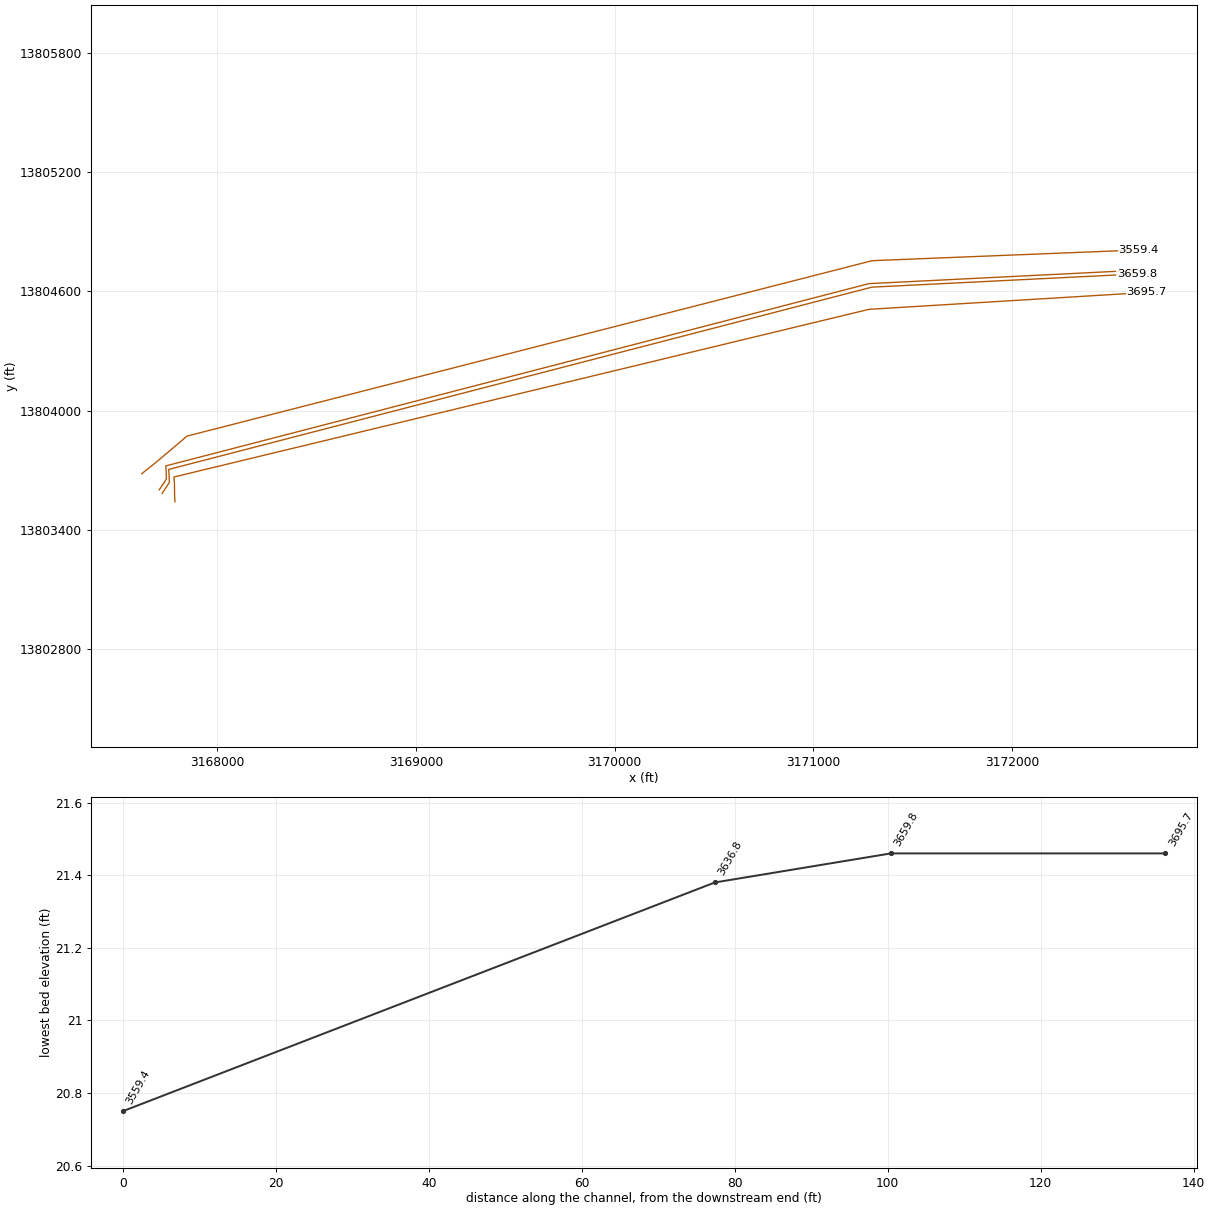
HEC-RAS study C106-08-00.PRJ: C106-08-00

--- C106-08-00.g01 (geometry) --- (continued)

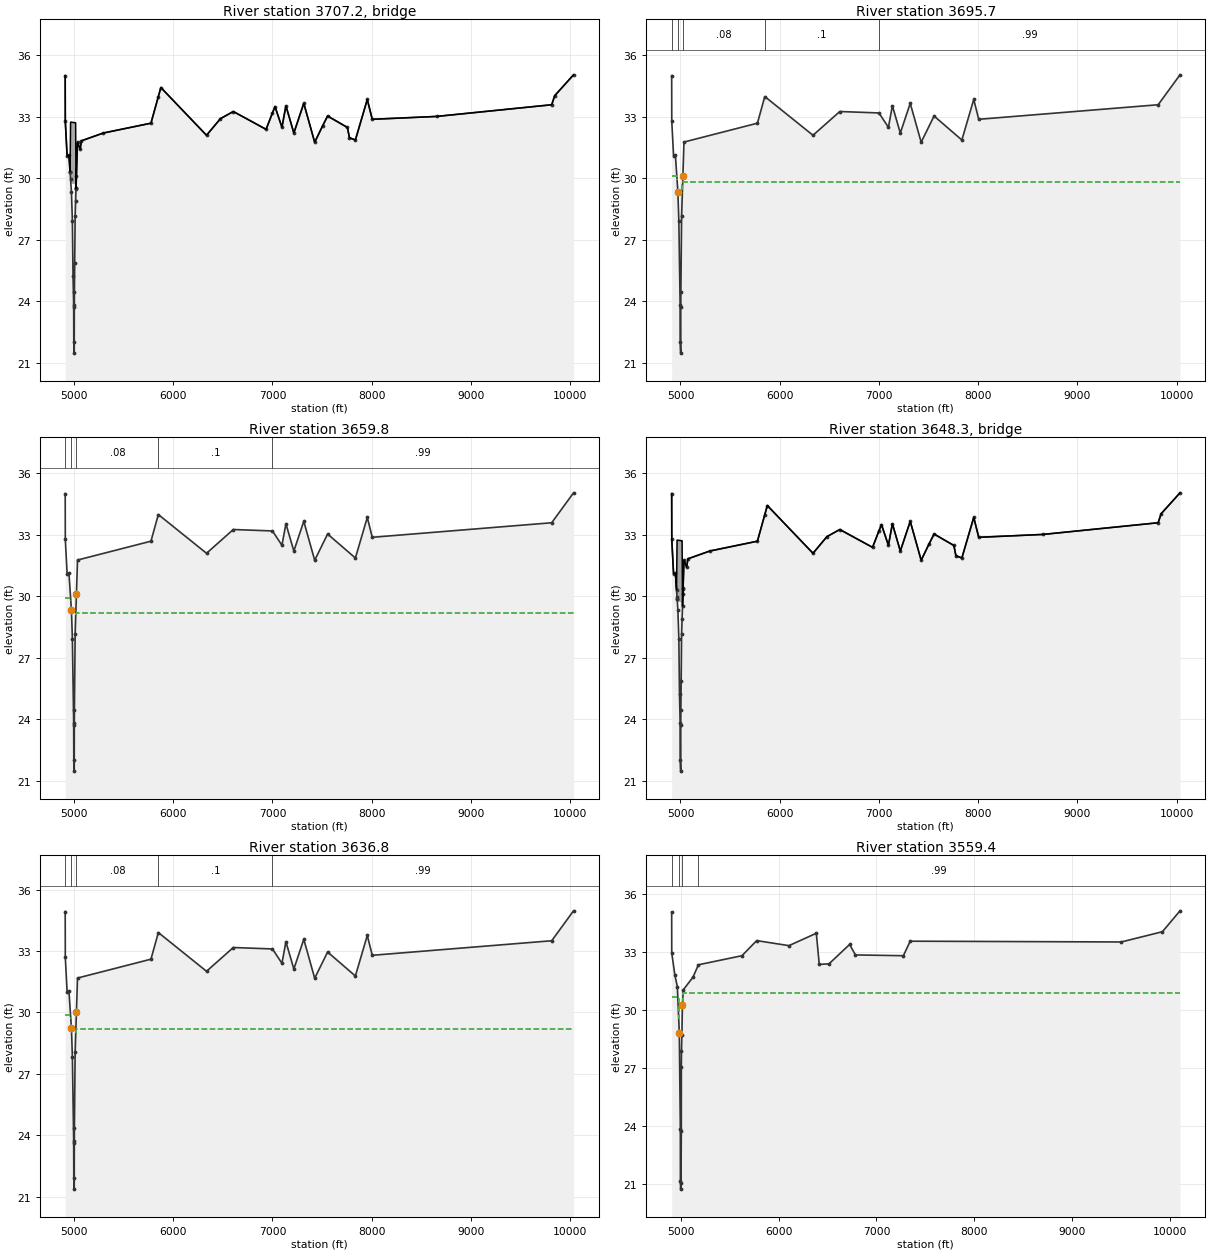
Type RM Length L Ch R = 3 ,3707.2  ,,,
BEGIN DESCRIPTION:
36" PIPELINE, SKEW ANGLE OF 25 DEGREES
END DESCRIPTION:
Bridge Culvert--1,0,-1,-1, 0
Deck Dist Width WeirC Skew NumUp NumDn MinLoCord MaxHiCord MaxSubmerge Is_Ogee
10,3,2.6,0, 52, 52, , , 0.95, 0, 1,1,,
  4911.5  4912.5 4930.71 4949.09 4960.26 4960.37 4960.46 4965.66 4974.12 4983.77
 4990.41 4996.69 4997.96 5002.51 5003.33 5004.24 5007.06  5011.7 5016.66 5020.45
 5020.56 5020.66 5024.44 5035.36 5062.21 5074.95  5295.5  5775.5    5850  5875.5
  6335.5  6475.5  6605.5  6935.5    7000  7025.5  7095.5  7135.5  7215.5  7315.5
  7425.5  7505.5  7555.5  7755.5  7775.5  7835.5  7955.5  8005.5  8653.7  9813.7
  9843.7 10033.7
      35   32.77   31.08   31.12   30.33   30.32   30.32   32.73   32.73   32.72
   32.72   32.71   32.71   32.71   32.71   32.71   32.71    32.7    32.7   29.49
   29.51   29.51   30.09   31.76   31.41   31.82    32.2   32.68   33.98   34.42
   32.09    32.9   33.25   32.38   33.18   33.49   32.48   33.53    32.2   33.65
   31.75   32.55   33.03   32.47   31.97   31.86   33.84   32.87   33.01   33.58
   34.02   35.04
      35   32.77   31.08   31.12   30.32   30.31   30.31   29.94   29.73   29.72
   29.72   29.71   29.71   29.71   29.71   29.71   29.71    29.7    29.7   29.48
    29.5   29.51   30.09   31.76   31.41   31.82    32.2   32.68   33.98   34.42
   32.09    32.9   33.25   32.38   33.18   33.49   32.48   33.53    32.2   33.65
   31.75   32.55   33.03   32.47   31.97   31.86   33.84   32.87   33.01   33.58
   34.02   35.04
  4911.5  4912.5 4930.71 4949.09 4960.26 4960.37 4960.46 4965.66 4974.12 4983.77
 4990.41 4996.69 4997.96 5002.51 5003.33 5004.24 5007.06  5011.7 5016.66 5020.45
 5020.56 5020.66 5024.44 5035.36 5062.21 5074.95  5295.5  5775.5    5850  5875.5
  6335.5  6475.5  6605.5  6935.5    7000  7025.5  7095.5  7135.5  7215.5  7315.5
  7425.5  7505.5  7555.5  7755.5  7775.5  7835.5  7955.5  8005.5  8653.7  9813.7
  9843.7 10033.7
      35   32.77   31.08   31.12   30.33   30.32   30.32   32.73   32.73   32.72
   32.72   32.71   32.71   32.71   32.71   32.71   32.71    32.7    32.7   29.49
   29.51   29.51   30.09   31.76   31.41   31.82    32.2   32.68   33.98   34.42
   32.09    32.9   33.25   32.38   33.18   33.49   32.48   33.53    32.2   33.65
   31.75   32.55   33.03   32.47   31.97   31.86   33.84   32.87   33.01   33.58
   34.02   35.04
      35   32.77   31.08   31.12   30.32   30.31   30.31   29.94   29.73   29.72
   29.72   29.71   29.71   29.71   29.71   29.71   29.71    29.7    29.7   29.48
    29.5   29.51   30.09   31.76   31.41   31.82    32.2   32.68   33.98   34.42
   32.09    32.9   33.25   32.38   33.18   33.49   32.48   33.53    32.2   33.65
   31.75   32.55   33.03   32.47   31.97   31.86   33.84   32.87   33.01   33.58
   34.02   35.04
BR Coef= 1 , 1 , 0 ,1.25, 0 ,,,0.8,0,2,0,
WSPro=,,,, 1 ,,,, 0 ,,,, 0 ,,,,-1 ,-1 ,-1 , 0 , 0 , 0 , 0 , 0
BR U #Sta/Elev= 52
  4911.5      35  4912.5   32.77 4930.71   31.08 4949.09   31.12 4960.26   30.32
 4960.37   30.31 4960.46   30.31 4965.66   29.94 4974.12   29.33 4983.77   27.92
 4990.41    25.2 4996.69   23.83 4997.96   21.99 5002.51   21.46 5003.33    23.7
 5004.24   24.44 5007.06   25.85  5011.7   28.14 5016.66    28.9 5020.45   29.48
 5020.56    29.5 5020.66   29.51 5024.44   30.09 5035.36   31.76 5062.21   31.41
 5074.95   31.82  5295.5    32.2  5775.5   32.68    5850   33.98  5875.5   34.42
  6335.5   32.09  6475.5    32.9  6605.5   33.25  6935.5   32.38    7000   33.18
  7025.5   33.49  7095.5   32.48  7135.5   33.53  7215.5    32.2  7315.5   33.65
  7425.5   31.75  7505.5   32.55  7555.5   33.03  7755.5   32.47  7775.5   31.97
  7835.5   31.86  7955.5   33.84  8005.5   32.87  8653.7   33.01  9813.7   33.58
  9843.7   34.02 10033.7   35.04
BR U #Mann= 5
  4911.5     .08 4974.12    .015 5024.44     .08    5850      .1    7000     .99
BR U Banks=4974.12,5024.44
BR D #Sta/Elev= 52
  4911.5      35  4912.5   32.77 4930.71   31.08 4949.09   31.12 4960.26   30.32
 4960.37   30.31 4960.46   30.31 4965.66   29.94 4974.12   29.33 4983.77   27.92
 4990.41    25.2 4996.69   23.83 4997.96   21.99 5002.51   21.46 5003.33    23.7
 5004.24   24.44 5007.06   25.85  5011.7   28.14 5016.66    28.9 5020.45   29.48
 5020.56    29.5 5020.66   29.51 5024.44   30.09 5035.36   31.76 5062.21   31.41
 5074.95   31.82  5295.5    32.2  5775.5   32.68    5850   33.98  5875.5   34.42
  6335.5   32.09  6475.5    32.9  6605.5   33.25  6935.5   32.38    7000   33.18
  7025.5   33.49  7095.5   32.48  7135.5   33.53  7215.5    32.2  7315.5   33.65
  7425.5   31.75  7505.5   32.55  7555.5   33.03  7755.5   32.47  7775.5   31.97
  7835.5   31.86  7955.5   33.84  8005.5   32.87  8653.7   33.01  9813.7   33.58
  9843.7   34.02 10033.7   35.04
BR D #Mann= 5
  4911.5     .08 4974.12    .015 5024.44     .08    5850      .1    7000     .99
BR D Banks=4974.12,5024.44
BC Design=,, 0 ,, 0 ,,,,,,
BC HTab HWMax=35.1
BC Use User HTab Curves=0
BC User HTab FreeFlow(D)= 0

Type RM Length L Ch R = 1 ,3695.7  ,36.2,35.9,34
BEGIN DESCRIPTION:
Downstream Section of Bridge/Culvert/Weir
END DESCRIPTION:
XS GIS Cut Line= 6
      3167787.02     13803541.71      3167785.15     13803569.77
      3167784.45     13803631.57      3167781.93     13803666.23
      3171279.98       13804510.      3172676.54     13804594.97
#Sta/Elev= 30
  4911.5      35  4912.5   32.77 4930.71   31.08 4949.09   31.12 4974.12   29.33
 4983.77   27.92 4996.69   23.83 4997.96   21.99 5002.51   21.46 5003.33    23.7
 5004.24   24.44  5011.7   28.14 5024.44   30.09 5035.36   31.76  5775.5   32.68
    5850   33.98  6335.5   32.09  6605.5   33.25    7000   33.18  7095.5   32.48
  7135.5   33.53  7215.5    32.2  7315.5   33.65  7425.5   31.75  7555.5   33.03
  7835.5   31.86  7955.5   33.84  8005.5   32.87  9813.7   33.58 10033.7   35.04
#Mann= 5 , 1 , 0
  4911.5     .08       0 4974.12    .015       0 5024.44     .08       0
    5850      .1       0    7000     .99       0
#XS Ineff= 2 , 0
       0  4965.7    30.1    5020       0    29.8
Permanent Ineff=
       F       F
Bank Sta=4974.12,5024.44
XS Rating Curve= 0 ,0
Exp/Cntr=0.5,0.3

Type RM Length L Ch R = 1 ,3659.8  ,23,23,23
BEGIN DESCRIPTION:
Upstream Section of Bridge/Culvert/Weir
END DESCRIPTION:
XS GIS Cut Line= 6
      3167722.55     13803584.17      3167758.66     13803638.33
      3167756.88     13803683.79       3167755.1      13803704.2
      3171294.13     13804621.58       3172627.6     13804687.94
#Sta/Elev= 30
  4911.5      35  4912.5   32.77 4930.71   31.08 4949.09   31.12 4974.12   29.33
 4983.77   27.92 4996.69   23.83 4997.96   21.99 5002.51   21.46 5003.33    23.7
 5004.24   24.44  5011.7   28.14 5024.44   30.09 5035.36   31.76  5775.5   32.68
    5850   33.98  6335.5   32.09  6605.5   33.25    7000   33.18  7095.5   32.48
  7135.5   33.53  7215.5    32.2  7315.5   33.65  7425.5   31.75  7555.5   33.03
  7835.5   31.86  7955.5   33.84  8005.5   32.87  9813.7   33.58 10033.7   35.04
#Mann= 5 , 1 , 0
  4911.5     .08       0 4974.12    .015       0 5024.44     .08       0
    5850      .1       0    7000     .99       0
#XS Ineff= 2 , 0
       0    4968    29.9  5017.8       0    29.2
Permanent Ineff=
       F       F
Bank Sta=4974.12,5024.44
XS Rating Curve= 0 ,0
Exp/Cntr=0.5,0.3

Type RM Length L Ch R = 3 ,3648.3  ,,,
BEGIN DESCRIPTION:
36" PIPELINE, SKEW ANGLE OF 25 DEGREES
END DESCRIPTION:
Bridge Culvert--1,0,-1,-1, 0
Deck Dist Width WeirC Skew NumUp NumDn MinLoCord MaxHiCord MaxSubmerge Is_Ogee
10,3,2.6,0, 52, 52, , , 0.95, 0, 1,1,,
  4911.5  4912.5 4930.71 4949.09 4960.46 4965.66 4966.77 4966.86 4974.12 4983.77
 4990.41 4996.69 4997.96 5002.51 5003.33 5004.24 5007.06  5011.7 5016.66 5020.66
 5024.44 5026.25 5026.36 5035.36 5062.21 5074.95  5295.5  5775.5    5850  5875.5
  6335.5  6475.5  6605.5  6935.5    7000  7025.5  7095.5  7135.5  7215.5  7315.5
  7425.5  7505.5  7555.5  7755.5  7775.5  7835.5  7955.5  8005.5  8653.7  9813.7
  9843.7 10033.7
      35   32.77   31.08   31.12   30.32   32.73   32.73   32.73   32.73   32.72
   32.72   32.71   32.71   32.71   32.71   32.71   32.71    32.7    32.7   29.52
   30.09   30.37   30.38   31.76   31.41   31.82    32.2   32.68   33.98   34.42
   32.09    32.9   33.25   32.38   33.18   33.49   32.48   33.53    32.2   33.65
   31.75   32.55   33.03   32.47   31.97   31.86   33.84   32.87   33.01   33.58
   34.02   35.04
      35   32.77   31.08   31.12   30.31   29.94   29.86   29.85   29.73   29.72
   29.72   29.71   29.71   29.71   29.71   29.71   29.71    29.7    29.7   29.51
   30.09   30.37   30.38   31.76   31.41   31.82    32.2   32.68   33.98   34.42
   32.09    32.9   33.25   32.38   33.18   33.49   32.48   33.53    32.2   33.65
   31.75   32.55   33.03   32.47   31.97   31.86   33.84   32.87   33.01   33.58
   34.02   35.04
  4911.5  4912.5 4930.71 4949.09 4960.46 4965.66 4966.77 4966.86 4974.12 4983.77
 4990.41 4996.69 4997.96 5002.51 5003.33 5004.24 5007.06  5011.7 5016.66 5020.66
 5024.44 5026.25 5026.36 5035.36 5062.21 5074.95  5295.5  5775.5    5850  5875.5
  6335.5  6475.5  6605.5  6935.5    7000  7025.5  7095.5  7135.5  7215.5  7315.5
  7425.5  7505.5  7555.5  7755.5  7775.5  7835.5  7955.5  8005.5  8653.7  9813.7
  9843.7 10033.7
      35   32.77   31.08   31.12   30.32   32.73   32.73   32.73   32.73   32.72
   32.72   32.71   32.71   32.71   32.71   32.71   32.71    32.7    32.7   29.52
   30.09   30.37   30.38   31.76   31.41   31.82    32.2   32.68   33.98   34.42
   32.09    32.9   33.25   32.38   33.18   33.49   32.48   33.53    32.2   33.65
   31.75   32.55   33.03   32.47   31.97   31.86   33.84   32.87   33.01   33.58
   34.02   35.04
      35   32.77   31.08   31.12   30.31   29.94   29.86   29.85   29.73   29.72
   29.72   29.71   29.71   29.71   29.71   29.71   29.71    29.7    29.7   29.51
   30.09   30.37   30.38   31.76   31.41   31.82    32.2   32.68   33.98   34.42
   32.09    32.9   33.25   32.38   33.18   33.49   32.48   33.53    32.2   33.65
   31.75   32.55   33.03   32.47   31.97   31.86   33.84   32.87   33.01   33.58
   34.02   35.04
BR Coef= 1 , 1 , 0 ,1.25, 0 ,,,0.8,0,2,0,
WSPro=,,,, 1 ,,,, 0 ,,,, 0 ,,,,-1 ,-1 ,-1 , 0 , 0 , 0 , 0 , 0
BR U #Sta/Elev= 52
  4911.5      35  4912.5   32.77 4930.71   31.08 4949.09   31.12 4960.46   30.31
 4965.66   29.94 4966.77   29.86 4966.86   29.85 4974.12   29.33 4983.77   27.92
 4990.41    25.2 4996.69   23.83 4997.96   21.99 5002.51   21.46 5003.33    23.7
 5004.24   24.44 5007.06   25.85  5011.7   28.14 5016.66    28.9 5020.66   29.51
 5024.44   30.09 5026.25   30.37 5026.36   30.38 5035.36   31.76 5062.21   31.41
 5074.95   31.82  5295.5    32.2  5775.5   32.68    5850   33.98  5875.5   34.42
  6335.5   32.09  6475.5    32.9  6605.5   33.25  6935.5   32.38    7000   33.18
  7025.5   33.49  7095.5   32.48  7135.5   33.53  7215.5    32.2  7315.5   33.65
  7425.5   31.75  7505.5   32.55  7555.5   33.03  7755.5   32.47  7775.5   31.97
  7835.5   31.86  7955.5   33.84  8005.5   32.87  8653.7   33.01  9813.7   33.58
  9843.7   34.02 10033.7   35.04
BR U #Mann= 5
  4911.5     .08 4974.12    .015 5024.44     .08    5850      .1    7000     .99
BR U Banks=4974.12,5024.44
BR D #Sta/Elev= 52
  4911.5      35  4912.5   32.77 4930.71   31.08 4949.09   31.12 4960.46   30.31
 4965.66   29.94 4966.77   29.86 4966.86   29.85 4974.12   29.33 4983.77   27.92
 4990.41    25.2 4996.69   23.83 4997.96   21.99 5002.51   21.46 5003.33    23.7
 5004.24   24.44 5007.06   25.85  5011.7   28.14 5016.66    28.9 5020.66   29.51
 5024.44   30.09 5026.25   30.37 5026.36   30.38 5035.36   31.76 5062.21   31.41
 5074.95   31.82  5295.5    32.2  5775.5   32.68    5850   33.98  5875.5   34.42
  6335.5   32.09  6475.5    32.9  6605.5   33.25  6935.5   32.38    7000   33.18
  7025.5   33.49  7095.5   32.48  7135.5   33.53  7215.5    32.2  7315.5   33.65
  7425.5   31.75  7505.5   32.55  7555.5   33.03  7755.5   32.47  7775.5   31.97
  7835.5   31.86  7955.5   33.84  8005.5   32.87  8653.7   33.01  9813.7   33.58
  9843.7   34.02 10033.7   35.04
BR D #Mann= 5
  4911.5     .08 4974.12    .015 5024.44     .08    5850      .1    7000     .99
BR D Banks=4974.12,5024.44
BC Design=,, 0 ,, 0 ,,,,,,
BC HTab HWMax=35.04
BC Use User HTab Curves=0
BC User HTab FreeFlow(D)= 0

Type RM Length L Ch R = 1 ,3636.8  ,78.9,77.4,77.1
BEGIN DESCRIPTION:
Downstream Section of Bridge/Culvert/Weir
END DESCRIPTION:
XS GIS Cut Line= 6
      3167707.81     13803601.82      3167743.92     13803655.99
      3167742.14     13803701.45      3167740.36     13803721.86
      3171279.39     13804639.24      3172612.85      13804705.6
#Sta/Elev= 30
  4911.5   34.92  4912.5   32.69 4930.71      31 4949.09   31.04 4974.12   29.25
 4983.77   27.84 4996.69   23.75 4997.96   21.91 5002.51   21.38 5003.33   23.62
 5004.24   24.36  5011.7   28.06 5024.44   30.01 5035.36   31.68  5775.5    32.6
    5850    33.9  6335.5   32.01  6605.5   33.17    7000    33.1  7095.5    32.4
  7135.5   33.45  7215.5   32.12  7315.5   33.57  7425.5   31.67  7555.5   32.95
  7835.5   31.78  7955.5   33.76  8005.5   32.79  9813.7    33.5 10033.7   34.96
#Mann= 5 , 1 , 0
  4911.5     .08       0 4974.12    .015       0 5024.44     .08       0
    5850      .1       0    7000     .99       0
#XS Ineff= 2 , 0
       0    4968    29.9  5017.8       0    29.2
Permanent Ineff=
       F       F
Bank Sta=4974.12,5024.44
XS Rating Curve= 0 ,0
Exp/Cntr=0.5,0.3

Type RM Length L Ch R = 1 ,3559.4  ,38,38,38
BEGIN DESCRIPTION:
Upstream Section of Bridge/Culvert/Weir
END DESCRIPTION:
XS GIS Cut Line= 6
      3167619.34     13803682.44      3167692.03     13803740.28
      3167740.28     13803781.06      3167847.93     13803872.06
      3171296.22     13804754.84      3172636.12     13804808.64
#Sta/Elev= 30
  4906.4   35.08  4907.1   32.96  4938.8   31.83  4964.5   31.22  4984.5   28.81
    4995   23.85  4995.5   21.18  4998.3   20.75  5001.9   21.06    5005   23.78
  5005.3   27.05  5006.6   27.89  5010.8   28.71  5016.2   30.29  5025.7   31.06
  5124.4   31.71  5179.8   32.35  5625.4   32.82  5775.4    33.6  6105.4   33.34
  6385.4   33.98  6415.4   32.37  6515.4    32.4  6725.4    33.4  6785.4   32.86
  7275.4   32.82  7345.4   33.57  9503.9   33.53  9923.9   34.06 10103.9   35.14
#Mann= 4 ,-1 , 0
  4906.4     .08       0  4984.5    .015       0  5016.2      .1       0
  5179.8     .99       0
#XS Ineff= 2 , 0
       0 4978.51    30.7 5017.09       0    30.9
Permanent Ineff=
       F       F
Bank Sta=4984.5,5016.2
XS Rating Curve= 0 ,0
Exp/Cntr=0.5,0.3