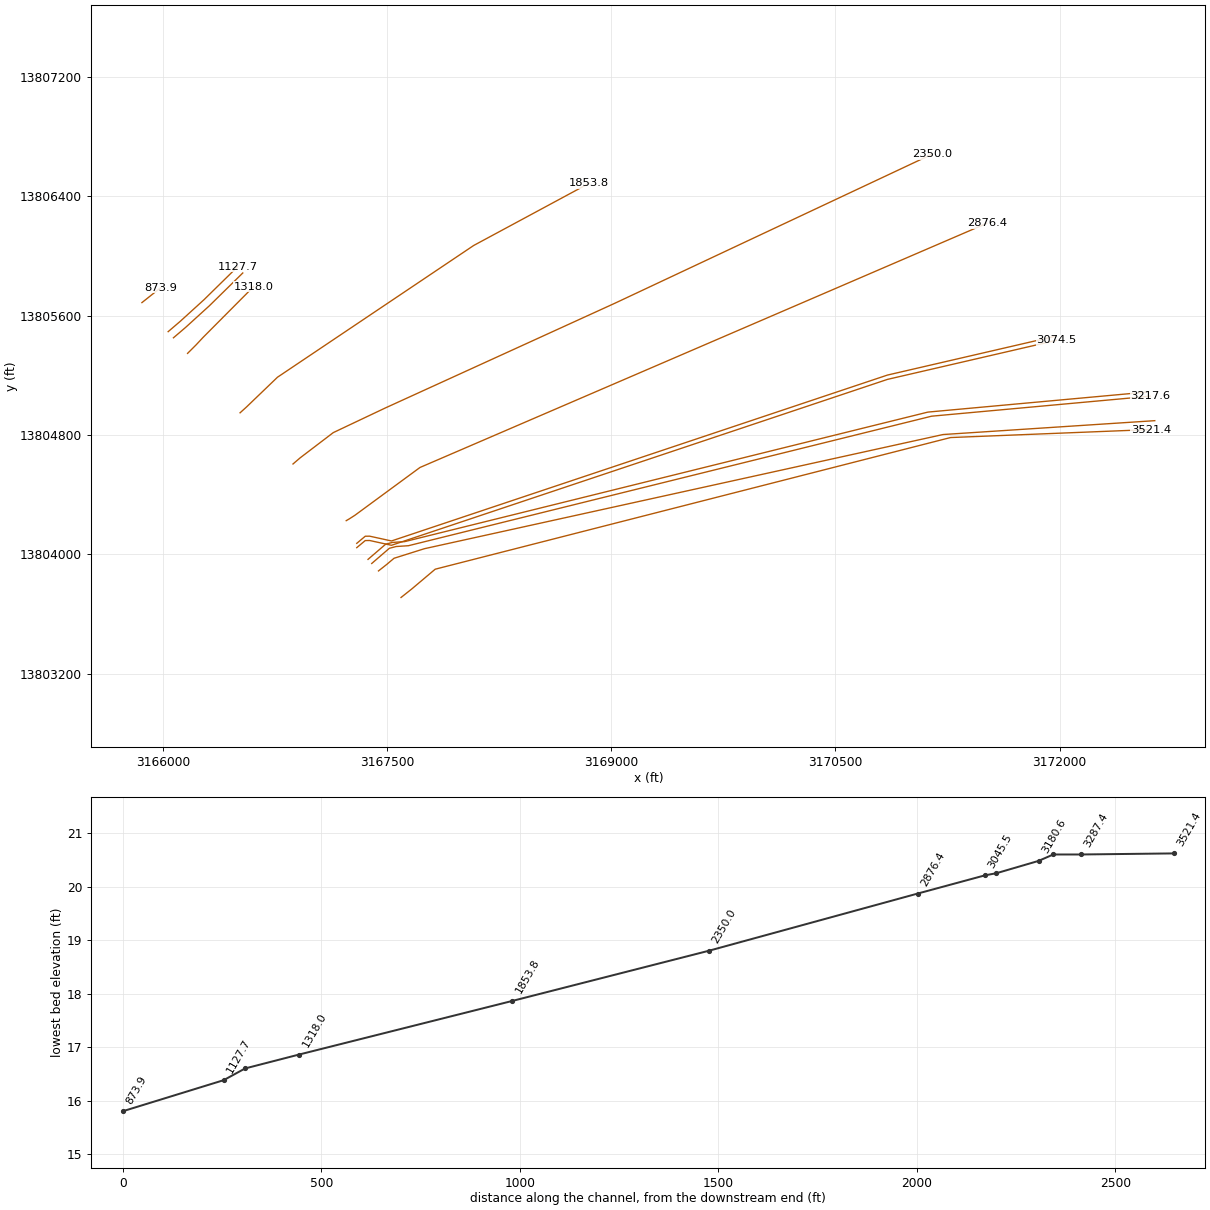
HEC-RAS study C106-08-00.PRJ: C106-08-00

--- C106-08-00.g01 (geometry) --- (continued)

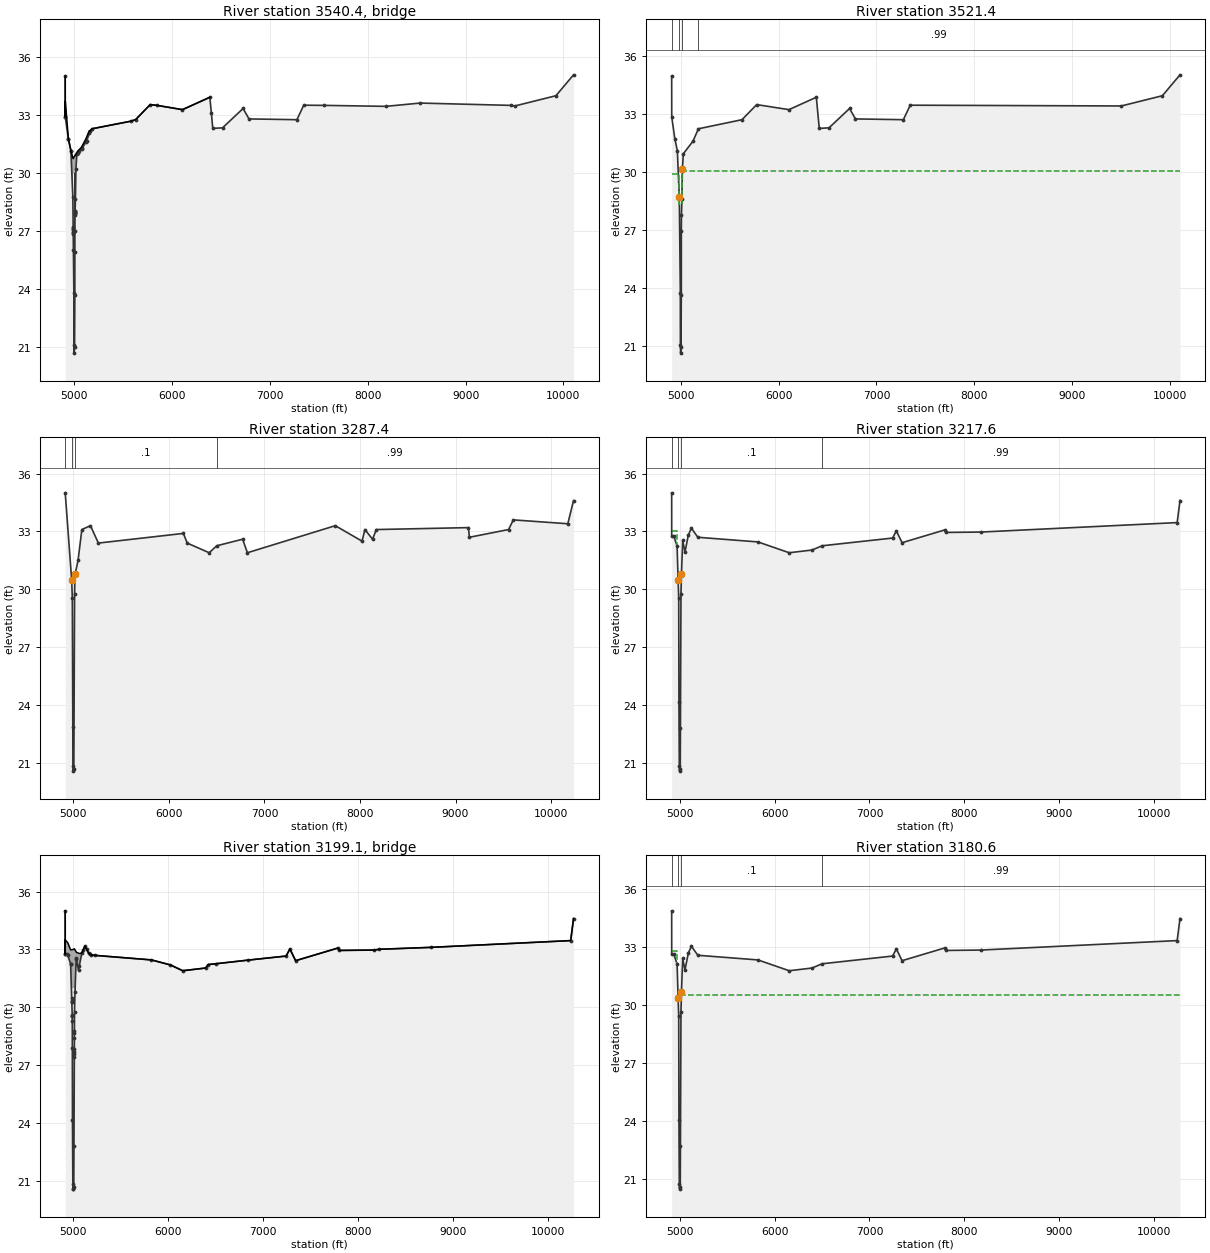
Type RM Length L Ch R = 3 ,3540.4  ,,,
BEGIN DESCRIPTION:
ACCESS ROAD 2
Structure ID: C68-4
END DESCRIPTION:
Bridge Culvert--1,0,-1,-1, 0
Deck Dist Width WeirC Skew NumUp NumDn MinLoCord MaxHiCord MaxSubmerge Is_Ogee
10,18,2.6,0, 48, 48, , , 0.95, 0, 1,1,,
  4906.4  4907.1  4907.2  4938.8  4939.2  4964.5  4964.7  4984.5  4987.7 4987.81
  4987.9    4988 4988.29  4988.4 4988.51  4990.2    4995  4995.5  4998.3  5001.9
    5005  5005.2  5005.3  5006.6    5007 5007.09  5007.2 5007.49  5007.6 5007.71
  5010.8  5016.2  5025.7  5033.7  5050.7  5073.5  5082.6  5117.1  5124.4  5154.3
  5161.1  5179.8  5575.4  5625.4  5775.4  5845.4  6105.4  6385.4
      35   32.88    33.7   31.77   31.75   31.15   31.13   30.78   30.73   30.73
   30.73   30.74   30.74   30.74   30.74   30.75   30.79    30.8   30.82   30.85
   30.87   30.88   30.88   30.89   30.89   30.89   30.89    30.9    30.9    30.9
   30.92   30.97   31.05   31.11    31.2   31.32   31.41   31.74   31.83   32.18
   32.15   32.27   32.66   32.74   33.52   33.48   33.26    33.9
                                                                                
   29.93   29.94   29.94   29.94   29.94   29.95   29.99      30   30.02   30.05
   30.07   30.08   30.08   30.09   30.09   30.09
                                                                                
                                                                
  4906.4  4907.1  4907.2  4938.8  4939.2  4964.5  4964.7  4984.5  4987.7 4987.81
  4987.9    4988 4988.29  4988.4 4988.51  4990.2    4995  4995.5  4998.3  5001.9
    5005  5005.2  5005.3  5006.6    5007 5007.09  5007.2 5007.49  5007.6 5007.71
  5010.8  5016.2  5025.7  5033.7  5050.7  5073.5  5082.6  5117.1  5124.4  5154.3
  5161.1  5179.8  5575.4  5625.4  5775.4  5845.4  6105.4  6385.4
      35   32.88    33.7   31.77   31.75   31.15   31.13   30.78   30.73   30.73
   30.73   30.74   30.74   30.74   30.74   30.75   30.79    30.8   30.82   30.85
   30.87   30.88   30.88   30.89   30.89   30.89   30.89    30.9    30.9    30.9
   30.92   30.97   31.05   31.11    31.2   31.32   31.41   31.74   31.83   32.18
   32.15   32.27   32.66   32.74   33.52   33.48   33.26    33.9
                                                                                
   29.88   29.89   29.89   29.89   29.89    29.9   29.94   29.95   29.97      30
   30.02   30.03   30.03   30.04   30.04   30.04
                                                                                
                                                                
Pier Skew, UpSta & Num, DnSta & Num=  ,4998.3, 2 ,4998.3, 2 , 0 , 0 , 0 ,,
      .8      .8
    19.7   31.02
      .8      .8
   19.65   30.97
Abutment Skew #Up #Dn= , 2 , 2
  4987.9  4990.2
   29.93      26
  4987.9  4990.2
   29.88   25.95
Abutment Skew #Up #Dn= , 2 , 2
  5005.3 5007.09
   26.97   30.09
  5005.3 5007.09
   26.92   30.04
BR Coef= 1 , 1 , 0 ,1.25, 0 ,,,0.8,0,2,0,
WSPro=,,,, 1 ,,,, 0 ,,,, 0 ,,,,-1 ,-1 ,-1 , 0 , 0 , 0 , 0 , 0
BR U #Sta/Elev= 62
  4906.4      35  4907.1   32.88  4907.2   32.88  4938.8   31.75  4939.2   31.74
  4964.5   31.14  4964.7   31.12  4984.5   28.73  4987.7    27.2 4987.81   27.14
  4987.9    27.1    4988   27.05 4988.29   26.91  4988.4   26.86 4988.51   26.81
  4990.2      26    4995   23.77  4995.5    21.1  4998.3   20.67  5001.9   20.98
    5005    23.7  5005.2   25.88  5005.3   26.97  5006.6   27.81    5007   27.89
 5007.09   27.91  5007.2   27.93 5007.49   27.98  5007.6   28.01 5007.71   28.03
  5010.8   28.63  5016.2   30.21  5025.7   30.98  5033.7   31.03  5050.7   31.13
  5073.5   31.24  5082.6   31.29  5117.1   31.57  5124.4   31.63  5154.3   32.05
  5161.1   32.15  5179.8   32.27  5575.4   32.66  5625.4   32.74  5775.4   33.52
  5845.4   33.48  6105.4   33.26  6385.4    33.9  6400.9   33.07  6415.4   32.29
  6515.4   32.32  6725.4   33.32  6785.4   32.78  7275.4   32.74  7345.4   33.49
  7555.4   33.48  8185.4   33.43  8535.4    33.6  9463.9   33.48  9503.9   33.45
  9923.9   33.98 10103.9   35.06
BR U #Mann= 4
  4906.4     .08  4984.5    .015  5016.2      .1  5179.8     .99
BR U Banks=4984.5,5016.2
BR D #Sta/Elev= 62
  4906.4   34.95  4907.1   32.83  4907.2   32.83  4938.8    31.7  4939.2   31.69
  4964.5   31.09  4964.7   31.07  4984.5   28.68  4987.7   27.15 4987.81   27.09
  4987.9   27.05    4988      27 4988.29   26.86  4988.4   26.81 4988.51   26.76
  4990.2   25.95    4995   23.72  4995.5   21.05  4998.3   20.62  5001.9   20.93
    5005   23.65  5005.2   25.83  5005.3   26.92  5006.6   27.76    5007   27.84
 5007.09   27.86  5007.2   27.88 5007.49   27.93  5007.6   27.96 5007.71   27.98
  5010.8   28.58  5016.2   30.16  5025.7   30.93  5033.7   30.98  5050.7   31.08
  5073.5   31.19  5082.6   31.24  5117.1   31.52  5124.4   31.58  5154.3      32
  5161.1    32.1  5179.8   32.22  5575.4   32.61  5625.4   32.69  5775.4   33.47
  5845.4   33.43  6105.4   33.21  6385.4   33.85  6400.9   33.02  6415.4   32.24
  6515.4   32.27  6725.4   33.27  6785.4   32.73  7275.4   32.69  7345.4   33.44
  7555.4   33.43  8185.4   33.38  8535.4   33.55  9463.9   33.43  9503.9    33.4
  9923.9   33.93 10103.9   35.01
BR D #Mann= 4
  4906.4     .08  4984.5    .015  5016.2      .1  5179.8     .99
BR D Banks=4984.5,5016.2
BC Design=,, 0 ,, 0 ,,,,,,
BC HTab HWMax=35.14
BC Use User HTab Curves=0
BC User HTab FreeFlow(D)= 0

Type RM Length L Ch R = 1 ,3521.4  ,235,234,220.4
BEGIN DESCRIPTION:
Downstream Section of Bridge/Culvert/Weir
END DESCRIPTION:
XS GIS Cut Line= 6
      3167593.85     13803710.62      3167666.55     13803768.46
       3167714.8     13803809.24      3167822.45     13803900.24
      3171270.74     13804783.02      3172610.63     13804836.83
#Sta/Elev= 30
  4906.4   34.95  4907.1   32.83  4938.8    31.7  4964.5   31.09  4984.5   28.68
    4995   23.72  4995.5   21.05  4998.3   20.62  5001.9   20.93    5005   23.65
  5005.3   26.92  5006.6   27.76  5010.8   28.58  5016.2   30.16  5025.7   30.93
  5124.4   31.58  5179.8   32.22  5625.4   32.69  5775.4   33.47  6105.4   33.21
  6385.4   33.85  6415.4   32.24  6515.4   32.27  6725.4   33.27  6785.4   32.73
  7275.4   32.69  7345.4   33.44  9503.9    33.4  9923.9   33.93 10103.9   35.01
#Mann= 4 ,-1 , 0
  4906.4     .08       0  4984.5    .015       0  5016.2      .1       0
  5179.8     .99       0
#XS Ineff= 2 , 0
       0  4985.5   29.89 5009.59       0   30.04
Permanent Ineff=
       F       F
Bank Sta=4984.5,5016.2
XS Rating Curve= 0 ,0
Exp/Cntr=0.5,0.3

Type RM Length L Ch R = 1 ,3287.4  ,69.7,69.8,75.8
BEGIN DESCRIPTION:
Cross Section 3287.4-Interpolted
END DESCRIPTION:
XS GIS Cut Line= 6
      3167443.04     13803888.71      3167496.37     13803930.82
       3167547.1     13803973.55      3167750.06     13804037.64
      3171220.55     13804803.25      3172637.45     13804896.25
#Sta/Elev= 30
    4914      35  4982.1   30.47  4988.4   29.54  4993.7   22.89  4994.5   20.84
  4996.6    20.6  5004.4    20.7  5012.1   29.77  5017.1   30.78  5048.3    31.5
  5088.3    33.1  5178.3    33.3  5261.1    32.4  6151.1    32.9  6191.1    32.4
  6421.1    31.9    6500   32.26  6771.1    32.6  6821.1    31.9  7741.1    33.3
  8021.1    32.5  8051.1    33.1  8131.1    32.6  8171.1    33.1    9135    33.2
    9145    32.7    9555    33.1    9605    33.6   10175    33.4   10235    34.6
#Mann= 4 , 1 , 0
    4914      .2       0  4982.1    .015       0  5017.1      .1       0
    6500     .99       0
Bank Sta=4982.1,5017.1
XS Rating Curve= 0 ,0
Exp/Cntr=0.5,0.3

Type RM Length L Ch R = 1 ,3217.6  ,37,37,37
BEGIN DESCRIPTION:
Upstream Section of Bridge/Culvert/Weir
END DESCRIPTION:
XS GIS Cut Line= 6
      3167397.78     13803938.65       3167515.7     13804040.43
      3167561.07     13804052.32      3167643.18     13804057.72
      3171144.33     13804926.32      3172607.06     13805060.42
#Sta/Elev= 30
    4914      35  4914.3   32.75  4936.9   32.75  4971.1   32.25  4982.1   30.47
  4988.4   29.54  4990.7   24.17  4994.5   20.84  4996.6    20.6  5004.4    20.7
  5006.4   22.84  5012.1   29.77  5017.1   30.78  5030.2   32.54  5054.3   31.94
  5089.3   32.81  5121.8   33.17  5190.1    32.7  5823.5   32.46  6153.5    31.9
  6393.5   32.04    6500   32.26  7243.5   32.66  7283.5   33.03  7343.5   32.42
  7793.5   33.08  7803.5   32.95  8173.5   32.97 10244.4   33.46 10274.4    34.6
#Mann= 4 , 1 , 0
    4914      .1       0  4982.1    .015       0  5017.1      .1       0
    6500     .99       0
#XS Ineff= 2 , 0
       0    4969      33  5016.2       0    30.5
Permanent Ineff=
       F       F
Bank Sta=4982.1,5017.1
XS Rating Curve= 0 ,0
Exp/Cntr=0.5,0.3

Type RM Length L Ch R = 3 ,3199.1  ,,,
BEGIN DESCRIPTION:
ACCESS ROAD 1
Structure ID: C68-3
END DESCRIPTION:
Bridge Culvert--1,0,-1,-1, 0
Deck Dist Width WeirC Skew NumUp NumDn MinLoCord MaxHiCord MaxSubmerge Is_Ogee
10,17,2.6,0, 60, 60, , , 0.95, 0, 1,1,,
    4914  4914.3  4914.4  4936.9  4941.3  4970.4  4971.1  4982.1 4983.19  4983.3
 4983.41 4988.01  4988.1  4988.4  4988.5  4989.1  4990.7  4994.5  4996.6  5000.9
  5004.4  5006.4  5010.2 5010.29  5010.4 5010.51    5011 5011.19  5011.3  5012.1
  5017.1  5030.2  5032.2  5054.3  5062.9  5089.3  5103.4  5121.8    5140  5160.2
  5175.5  5190.1  5227.2  5823.5  6023.5  6153.5  6393.5  6423.5    6500  6843.5
  7243.5  7283.5  7343.5  7793.5  7803.5  8173.5  8223.5  8774.4 10244.4 10274.4
      35   32.75    33.5   33.37   33.35   32.98   32.98   32.99   32.99   32.99
   32.99   32.99   32.99   32.99   32.99   32.99   32.99      33      33   33.01
   33.02   33.02   33.03   33.03   33.03   33.03   33.03   33.02   33.02   33.02
   32.98   32.87   32.85   32.81   32.79   32.82   32.98   33.18   33.01   32.82
   32.76   32.71    32.7   32.46    32.2    31.9   32.04   32.22   32.26   32.45
   32.66   33.03   32.42   33.08   32.95   32.97   33.01   33.11   33.46    34.6
      35   32.75   32.75   32.75   32.69   32.26   32.25   30.47   30.31   30.29
   30.28    29.6   30.99   30.99   30.99   30.99   30.99      31      31   31.01
   31.02   31.02   31.03   31.03   31.03   31.03   31.03   31.02    28.8   29.77
   30.78   32.54   32.49   31.94   32.15   32.81   32.97   33.17      33   32.81
   32.75    32.7   32.69   32.46    32.2    31.9   32.04   32.22   32.26   32.45
   32.66   33.03   32.42   33.08   32.95   32.97   33.01   33.11   33.46    34.6
    4914  4914.3  4914.4  4936.9  4941.3  4970.4  4971.1  4982.1 4983.19  4983.3
 4983.41 4988.01  4988.1  4988.4  4988.5  4989.1  4990.7  4994.5  4996.6  5000.9
  5004.4  5006.4  5010.2 5010.29  5010.4 5010.51    5011 5011.19  5011.3  5012.1
  5017.1  5030.2  5032.2  5054.3  5062.9  5089.3  5103.4  5121.8    5140  5160.2
  5175.5  5190.1  5227.2  5823.5  6023.5  6153.5  6393.5  6423.5    6500  6843.5
  7243.5  7283.5  7343.5  7793.5  7803.5  8173.5  8223.5  8774.4 10244.4 10274.4
      35   32.75    33.5   33.37   33.35   32.98   32.98   32.99   32.99   32.99
   32.99   32.99   32.99   32.99   32.99   32.99   32.99      33      33   33.01
   33.02   33.02   33.03   33.03   33.03   33.03   33.03   33.02   33.02   33.02
   32.98   32.87   32.85   32.81   32.79   32.82   32.98   33.18   33.01   32.82
   32.76   32.71    32.7   32.46    32.2    31.9   32.04   32.22   32.26   32.45
   32.66   33.03   32.42   33.08   32.95   32.97   33.01   33.11   33.46    34.6
    34.9   32.65   32.65   32.65   32.59   32.16   32.15   30.37   30.21   30.19
   30.18    29.5   30.89   30.89   30.89   30.89   30.89    30.9    30.9   30.91
   30.92   30.92   30.93   30.93   30.93   30.93   30.93   30.92    28.7   29.67
   30.68   32.44   32.39   31.84   32.05   32.71   32.87   33.07    32.9   32.71
   32.65    32.6   32.59   32.36    32.1    31.8   31.94   32.12   32.16   32.35
   32.56   32.93   32.32   32.98   32.85   32.87   32.91   33.01   33.36    34.5
BR Coef= 1 , 1 , 0 ,1.25, 0 ,,,0.8,0,2,0,
WSPro=,,,, 1 ,,,, 0 ,,,, 0 ,,,,-1 ,-1 ,-1 , 0 , 0 , 0 , 0 , 0
BR U #Sta/Elev= 60
    4914      35  4914.3   32.75  4914.4   32.75  4936.9   32.75  4941.3   32.69
  4970.4   32.26  4971.1   32.25  4982.1   30.47 4983.19   30.31  4983.3   30.29
 4983.41   30.28 4988.01    29.6  4988.1   29.58  4988.4   29.54  4988.5   29.31
  4989.1   27.91  4990.7   24.17  4994.5   20.84  4996.6    20.6  5000.9    20.6
  5004.4    20.7  5006.4   22.84  5010.2   27.46 5010.29   27.57  5010.4    27.7
 5010.51   27.84    5011   28.43 5011.19   28.66  5011.3    28.8  5012.1   29.77
  5017.1   30.78  5030.2   32.54  5032.2   32.49  5054.3   31.94  5062.9   32.15
  5089.3   32.81  5103.4   32.97  5121.8   33.17    5140      33  5160.2   32.81
  5175.5   32.75  5190.1    32.7  5227.2   32.69  5823.5   32.46  6023.5    32.2
  6153.5    31.9  6393.5   32.04  6423.5   32.22    6500   32.26  6843.5   32.45
  7243.5   32.66  7283.5   33.03  7343.5   32.42  7793.5   33.08  7803.5   32.95
  8173.5   32.97  8223.5   33.01  8774.4   33.11 10244.4   33.46 10274.4    34.6
BR U #Mann= 4
    4914      .1  4982.1    .015  5017.1      .1    6500     .99
BR U Banks=4982.1,5017.1
BR D #Sta/Elev= 60
    4914    34.9  4914.3   32.65  4914.4   32.65  4936.9   32.65  4941.3   32.59
  4970.4   32.16  4971.1   32.15  4982.1   30.37 4983.19   30.21  4983.3   30.19
 4983.41   30.18 4988.01    29.5  4988.1   29.48  4988.4   29.44  4988.5   29.21
  4989.1   27.81  4990.7   24.07  4994.5   20.74  4996.6    20.5  5000.9    20.5
  5004.4    20.6  5006.4   22.74  5010.2   27.36 5010.29   27.47  5010.4    27.6
 5010.51   27.74    5011   28.33 5011.19   28.56  5011.3    28.7  5012.1   29.67
  5017.1   30.68  5030.2   32.44  5032.2   32.39  5054.3   31.84  5062.9   32.05
  5089.3   32.71  5103.4   32.87  5121.8   33.07    5140    32.9  5160.2   32.71
  5175.5   32.65  5190.1    32.6  5227.2   32.59  5823.5   32.36  6023.5    32.1
  6153.5    31.8  6393.5   31.94  6423.5   32.12    6500   32.16  6843.5   32.35
  7243.5   32.56  7283.5   32.93  7343.5   32.32  7793.5   32.98  7803.5   32.85
  8173.5   32.87  8223.5   32.91  8774.4   33.01 10244.4   33.36 10274.4    34.5
BR D #Mann= 4
    4914      .1  4982.1    .015  5017.1      .1    6500     .99
BR D Banks=4982.1,5017.1
BC Design=,, 0 ,, 0 ,,,,,,
BC HTab HWMax=35
BC Use User HTab Curves=0
BC User HTab FreeFlow(D)= 0

Type RM Length L Ch R = 1 ,3180.6  ,116.2,106.1,79.9
BEGIN DESCRIPTION:
Downstream Section of Bridge/Culvert/Weir
END DESCRIPTION:
XS GIS Cut Line= 6
      3167372.97     13803966.09      3167490.88     13804067.87
      3167536.25     13804079.76      3167618.36     13804085.16
      3171119.51     13804953.76      3172582.24     13805087.86
#Sta/Elev= 30
    4914   34.88  4914.3   32.63  4936.9   32.63  4971.1   32.13  4982.1   30.35
  4988.4   29.42  4990.7   24.05  4994.5   20.72  4996.6   20.48  5004.4   20.58
  5006.4   22.72  5012.1   29.65  5017.1   30.66  5030.2   32.42  5054.3   31.82
  5089.3   32.69  5121.8   33.05  5190.1   32.58  5823.5   32.34  6153.5   31.78
  6393.5   31.92    6500   32.14  7243.5   32.54  7283.5   32.91  7343.5    32.3
  7793.5   32.96  7803.5   32.83  8173.5   32.85 10244.4   33.34 10274.4   34.48
#Mann= 4 , 1 , 0
    4914      .1       0  4982.1    .015       0  5017.1      .1       0
    6500     .99       0
#XS Ineff= 2 , 0
       0    4969    32.8  5016.2       0    30.5
Permanent Ineff=
       F       F
Bank Sta=4982.1,5017.1
XS Rating Curve= 0 ,0
Exp/Cntr=0.5,0.3

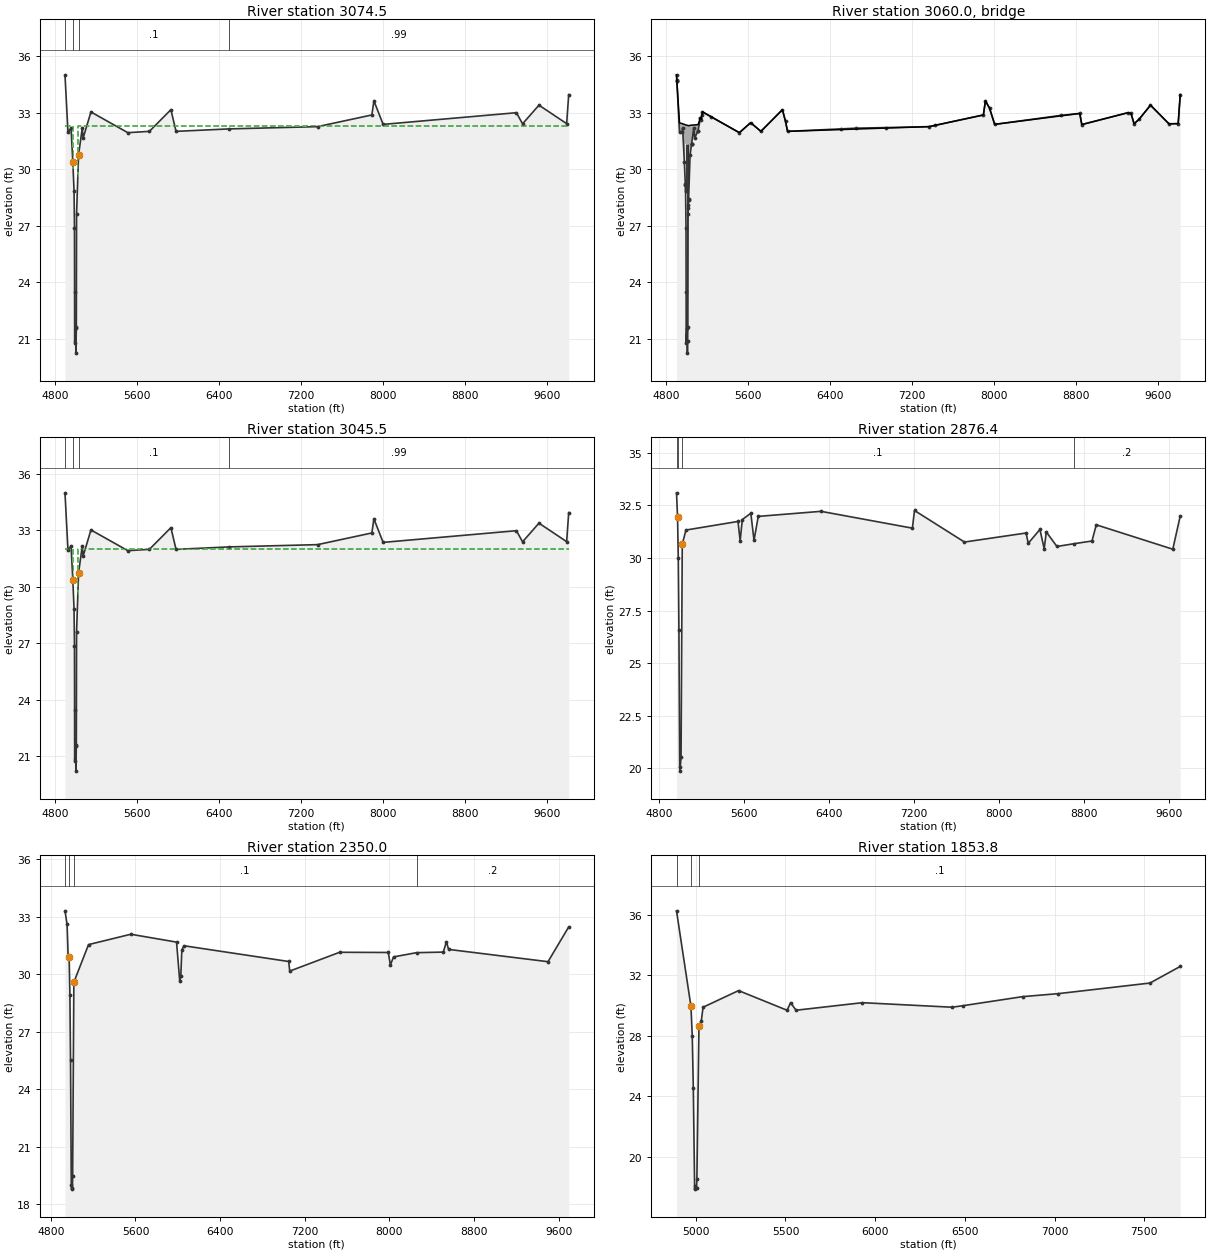
Type RM Length L Ch R = 1 ,3074.5  ,29,29,29
BEGIN DESCRIPTION:
Upstream Section of Bridge/Culvert/Weir
END DESCRIPTION:
XS GIS Cut Line= 6
      3167297.57     13804044.63      3167354.38      13804092.3
      3167383.64     13804092.71      3167529.91      13804060.6
      3170848.52     13805172.97      3171978.51      13805434.9
#Sta/Elev= 30
  4899.9   35.02  4929.1   31.99  4959.4   32.19  4976.4    30.4  4988.4   28.86
  4992.5   26.91  4993.8    23.5  4994.3   20.81  5002.8   21.57  5006.2   20.25
  5010.7   21.65  5012.9   27.62  5032.3   30.76  5068.6    32.2  5076.9   31.66
  5153.1   33.05  5513.1   31.95  5723.1   32.02  5933.1   33.17  5983.1   32.02
    6500   32.15  7363.1   32.27  7893.1   32.89  7913.1   33.64  8003.1   32.39
  9303.1   33.01  9363.1   32.42  9523.1   33.41  9793.1   32.43  9813.1   33.97
#Mann= 4 ,-1 , 0
  4899.9      .1       0  4976.4    .015       0  5032.3      .1       0
    6500     .99       0
#XS Ineff= 2 , 0
       0  4979.5    32.3    5025       0    32.3
Permanent Ineff=
       F       F
Bank Sta=4976.4,5032.3
XS Rating Curve= 0 ,0
Exp/Cntr=0.5,0.3

Type RM Length L Ch R = 3 ,3060.0  ,,,
BEGIN DESCRIPTION:
RAILWAY
Structure ID: C68-2
END DESCRIPTION:
Bridge Culvert--1,0,-1,-1, 0
Deck Dist Width WeirC Skew NumUp NumDn MinLoCord MaxHiCord MaxSubmerge Is_Ogee
10,9,2.6,0, 37, 37, , , 0.95, 0, 1,1,,
  4899.9  4929.1  4955.9  4959.4  4976.4 4985.71  4985.8 5017.69  5017.8  5032.3
  5068.6  5076.9  5110.6  5133.7  5140.3  5153.1  5513.1  5623.1  5723.1  5933.1
  5963.1  5983.1  7363.1  7893.1  7913.1  7953.1  8003.1  8833.1  8853.1  9303.1
  9333.1  9363.1  9413.1  9523.1  9703.1  9793.1  9813.1
      35   32.45   32.41    32.4   32.37   32.35   32.35    32.3    32.3   32.32
   32.34   32.34   32.36   32.73   32.63   33.04   31.93   32.46      32   33.15
   32.53      32   32.25   32.87   33.62   33.23   32.37   32.95   32.36   32.99
   32.95    32.4   32.65   33.39    32.4   32.41   33.95
      35   31.97   31.94   32.17   30.38   29.19   31.35    31.3   28.39   30.74
   32.18   31.64   32.04   32.72   32.62   33.03   31.93   32.46      32   33.15
   32.53      32   32.25   32.87   33.62   33.23   32.37   32.95   32.36   32.99
   32.95    32.4   32.65   33.39    32.4   32.41   33.95
  4899.9  4929.1  4955.9  4959.4  4976.4 4985.71  4985.8 5017.69  5017.8  5032.3
  5068.6  5076.9  5110.6  5133.7  5140.3  5153.1  5513.1  5623.1  5723.1  5933.1
  5963.1  5983.1  7363.1  7893.1  7913.1  7953.1  8003.1  8833.1  8853.1  9303.1
  9333.1  9363.1  9413.1  9523.1  9703.1  9793.1  9813.1
      35   32.45   32.41    32.4   32.37   32.35   32.35    32.3    32.3   32.32
   32.34   32.34   32.36   32.73   32.63   33.04   31.93   32.46      32   33.15
   32.53      32   32.25   32.87   33.62   33.23   32.37   32.95   32.36   32.99
   32.95    32.4   32.65   33.39    32.4   32.41   33.95
      35   31.97   31.94   32.17   30.38   29.19   31.35    31.3   28.39   30.74
   32.18   31.64   32.04   32.72   32.62   33.03   31.93   32.46      32   33.15
   32.53      32   32.25   32.87   33.62   33.23   32.37   32.95   32.36   32.99
   32.95    32.4   32.65   33.39    32.4   32.41   33.95
Pier Skew, UpSta & Num, DnSta & Num=  ,4988.4, 2 ,4988.4, 2 , 0 , 0 , 0 ,,
       1       1
    27.6   32.35
       1       1
    27.6   32.35
Pier Skew, UpSta & Num, DnSta & Num=  ,5000.9, 2 ,5000.9, 2 , 0 , 0 , 0 ,,
       1       1
    20.5   32.33
       1       1
    20.5   32.33
Pier Skew, UpSta & Num, DnSta & Num=  ,5013.3, 2 ,5013.3, 2 , 0 , 0 , 0 ,,
       1       1
   26.33    32.3
       1       1
   26.33    32.3
Abutment Skew #Up #Dn= , 2 , 2
  4985.6    4987
    31.5   28.92
  4985.6    4987
    31.6   28.92
Abutment Skew #Up #Dn= , 2 , 2
    5016 5017.89
   28.07    31.5
    5016 5017.89
   28.07    31.5
BR Coef= 1 , 1 , 0 ,1.25, 0 ,,,0.8,-1,2,0,
WSPro=,,,, 1 ,,,, 0 ,,,, 0 ,,,,-1 ,-1 ,-1 , 0 , 0 , 0 , 0 , 0
BR U #Sta/Elev= 65
  4899.9      35 4902.79    34.7  4902.9   34.69 4903.01   34.68  4929.1   31.97
  4955.9   31.94  4959.4   32.17  4976.4   30.38 4985.71   29.19  4985.8   29.17
  4987.8   28.92  4988.4   28.84  4992.5   26.89  4993.8   23.48  4994.3   20.79
  5000.9   21.56  5002.8   21.55  5006.2   20.23    5008   20.86  5010.7   21.63
  5012.9    27.6    5015   27.94  5015.8   28.07 5017.69   28.38  5017.8   28.39
  5032.3   30.74 5046.69   31.31  5046.8   31.32 5046.91   31.32  5068.6   32.18
  5076.9   31.64  5109.8   32.03  5110.6   32.04  5132.9    32.7  5133.7   32.72
  5140.3   32.62    5148   32.87  5153.1   33.03  5240.1   32.76  5513.1   31.93
  5623.1   32.46  5723.1      32  5933.1   33.15  5963.1   32.53  5983.1      32
    6500   32.13  6653.1   32.17  6943.1    32.2  7363.1   32.25  7423.1   32.32
  7893.1   32.87  7913.1   33.62  7953.1   33.23  8003.1   32.37  8653.1   32.85
  8833.1   32.95  8853.1   32.36  9303.1   32.99  9333.1   32.95  9363.1    32.4
  9413.1   32.65  9523.1   33.39  9703.1    32.4  9793.1   32.41  9813.1   33.95
BR U #Mann= 4
  4899.9      .1  4976.4    .015  5032.3      .1    6500     .99
BR U Banks=4976.4,5032.3
BR D #Sta/Elev= 65
  4899.9      35 4902.79    34.7  4902.9   34.69 4903.01   34.68  4929.1   31.97
  4955.9   31.94  4959.4   32.17  4976.4   30.38 4985.71   29.19  4985.8   29.17
  4987.8   28.92  4988.4   28.84  4992.5   26.89  4993.8   23.48  4994.3   20.79
  5000.9   21.56  5002.8   21.55  5006.2   20.23    5008   20.86  5010.7   21.63
  5012.9    27.6    5015   27.94  5015.8   28.07 5017.69   28.38  5017.8   28.39
  5032.3   30.74 5046.69   31.31  5046.8   31.32 5046.91   31.32  5068.6   32.18
  5076.9   31.64  5109.8   32.03  5110.6   32.04  5132.9    32.7  5133.7   32.72
  5140.3   32.62    5148   32.87  5153.1   33.03  5240.1   32.76  5513.1   31.93
  5623.1   32.46  5723.1      32  5933.1   33.15  5963.1   32.53  5983.1      32
    6500   32.13  6653.1   32.17  6943.1    32.2  7363.1   32.25  7423.1   32.32
  7893.1   32.87  7913.1   33.62  7953.1   33.23  8003.1   32.37  8653.1   32.85
  8833.1   32.95  8853.1   32.36  9303.1   32.99  9333.1   32.95  9363.1    32.4
  9413.1   32.65  9523.1   33.39  9703.1    32.4  9793.1   32.41  9813.1   33.95
BR D #Mann= 4
  4899.9      .1  4976.4    .015  5032.3      .1    6500     .99
BR D Banks=4976.4,5032.3
BC Design=,, 0 ,, 0 ,,,,,,
BC HTab HWMax=35.02
BC Use User HTab Curves=0
BC User HTab FreeFlow(D)= 0

Type RM Length L Ch R = 1 ,3045.5  ,123.4,169.1,183.1
BEGIN DESCRIPTION:
Downstream Section of Bridge/Culvert/Weir
END DESCRIPTION:
XS GIS Cut Line= 6
      3167297.57     13804073.63      3167354.38      13804121.3
      3167383.64     13804121.71      3167529.91      13804089.6
      3170848.52     13805201.97      3171978.51      13805463.9
#Sta/Elev= 30
  4899.9   34.98  4929.1   31.95  4959.4   32.15  4976.4   30.36  4988.4   28.82
  4992.5   26.87  4993.8   23.46  4994.3   20.77  5002.8   21.53  5006.2   20.21
  5010.7   21.61  5012.9   27.58  5032.3   30.72  5068.6   32.16  5076.9   31.62
  5153.1   33.01  5513.1   31.91  5723.1   31.98  5933.1   33.13  5983.1   31.98
    6500   32.11  7363.1   32.23  7893.1   32.85  7913.1    33.6  8003.1   32.35
  9303.1   32.97  9363.1   32.38  9523.1   33.37  9793.1   32.39  9813.1   33.93
#Mann= 4 ,-1 , 0
  4899.9      .1       0  4976.4    .015       0  5032.3      .1       0
    6500     .99       0
#XS Ineff= 2 , 0
       0    4975      32    5025       0      32
Permanent Ineff=
       F       F
Bank Sta=4976.4,5032.3
XS Rating Curve= 0 ,0
Exp/Cntr=0.5,0.3

Type RM Length L Ch R = 1 ,2876.4  ,523.4,526.4,578.4
BEGIN DESCRIPTION:
Cross Section 2876.4-Interpolated
END DESCRIPTION:
XS GIS Cut Line= 5
      3167227.09     13804225.71      3167248.02     13804237.92
       3167285.4     13804261.95      3167720.68     13804582.41
      3171512.47     13806219.27
#Sta/Elev= 30
  4963.6    33.1  4973.3   31.96  4980.5   29.99  4986.3   26.59  4993.6   20.07
  4996.3   19.87  5006.3   20.54  5017.7   30.65  5052.2   31.33  5542.2   31.74
  5562.2   30.82  5582.8   31.83  5662.8   32.13  5692.8   30.84  5732.8   31.98
  6322.8   32.22  7182.8   31.42  7202.8   32.26  7672.8   30.76  8252.8   31.19
  8272.8    30.7  8382.8   31.36  8422.8   30.44  8442.8   31.24  8542.8   30.55
  8702.4   30.68  8872.8   30.81  8912.8   31.58  9632.8   30.42  9702.8      32
#Mann= 4 ,-1 , 0
  4963.6      .1       0  4973.3    .015       0  5017.7      .1       0
  8702.4      .2       0
Bank Sta=4973.3,5017.7
XS Rating Curve= 0 ,0
Exp/Cntr=0.3,0.1

Type RM Length L Ch R = 1 ,2350.0  ,494.4,496.2,499.9
BEGIN DESCRIPTION:
Cross Section 2350.0-Interpolated
END DESCRIPTION:
XS GIS Cut Line= 6
      3166870.93     13804605.76      3166918.43     13804646.66
      3167140.52      13804816.2       3167486.1      13804980.2
      3169024.56     13805683.59      3171146.71     13806682.87
#Sta/Elev= 30
  4933.9    33.3  4953.9   32.59  4963.9    30.9  4973.3   30.89  4980.5   28.92
  4986.3   25.52  4993.6      19  4996.3    18.8  5004.3   18.88  5006.3   19.47
  5017.8   29.58  5156.6   31.54    5556   32.08  5988.6   31.67  6018.6   29.65
  6028.6   29.88  6038.6   31.26  6058.6   31.48  7048.6   30.66  7058.6   30.16
  7530.2   31.14  7990.2   31.13  8010.2   30.48  8040.2    30.9  8257.7   31.12
  8510.2   31.15  8540.2   31.69  8560.2   31.29  9500.2   30.65  9695.8   32.46
#Mann= 4 , 1 , 0
  4933.9      .1       0  4973.3    .015       0  5017.8      .1       0
  8257.7      .2       0
Bank Sta=4973.3,5017.8
XS Rating Curve= 0 ,0
Exp/Cntr=0.3,0.1

Type RM Length L Ch R = 1 ,1853.8  ,535.4,535.8,540.7
BEGIN DESCRIPTION:
Cross Section 1853.8-Interpolated
END DESCRIPTION:
XS GIS Cut Line= 5
      3166516.73     13804948.97      3166559.73     13804987.93
      3166767.07     13805187.53      3168080.15      13806071.1
      3168853.27     13806488.34
#Sta/Elev= 23
  4892.7   36.28  4973.3   29.95  4980.5   27.98  4986.3   24.58  4993.6   18.06
  4996.3   17.86  4997.9   17.92  5004.3   17.94  5006.3   18.53  5017.8   28.64
  5030.8      29  5040.8    29.9  5238.6      31  5508.6    29.7  5528.6    30.2
  5558.6    29.7  5928.6    30.2  6428.6    29.9  6488.6      30  6821.2    30.6
  7021.2    30.8  7531.2    31.5  7699.8    32.6
#Mann= 3 , 1 , 0
  4892.7      .2       0  4973.3    .015       0  5017.8      .1       0
Bank Sta=4973.3,5017.8
XS Rating Curve= 0 ,0
Exp/Cntr=0.3,0.1

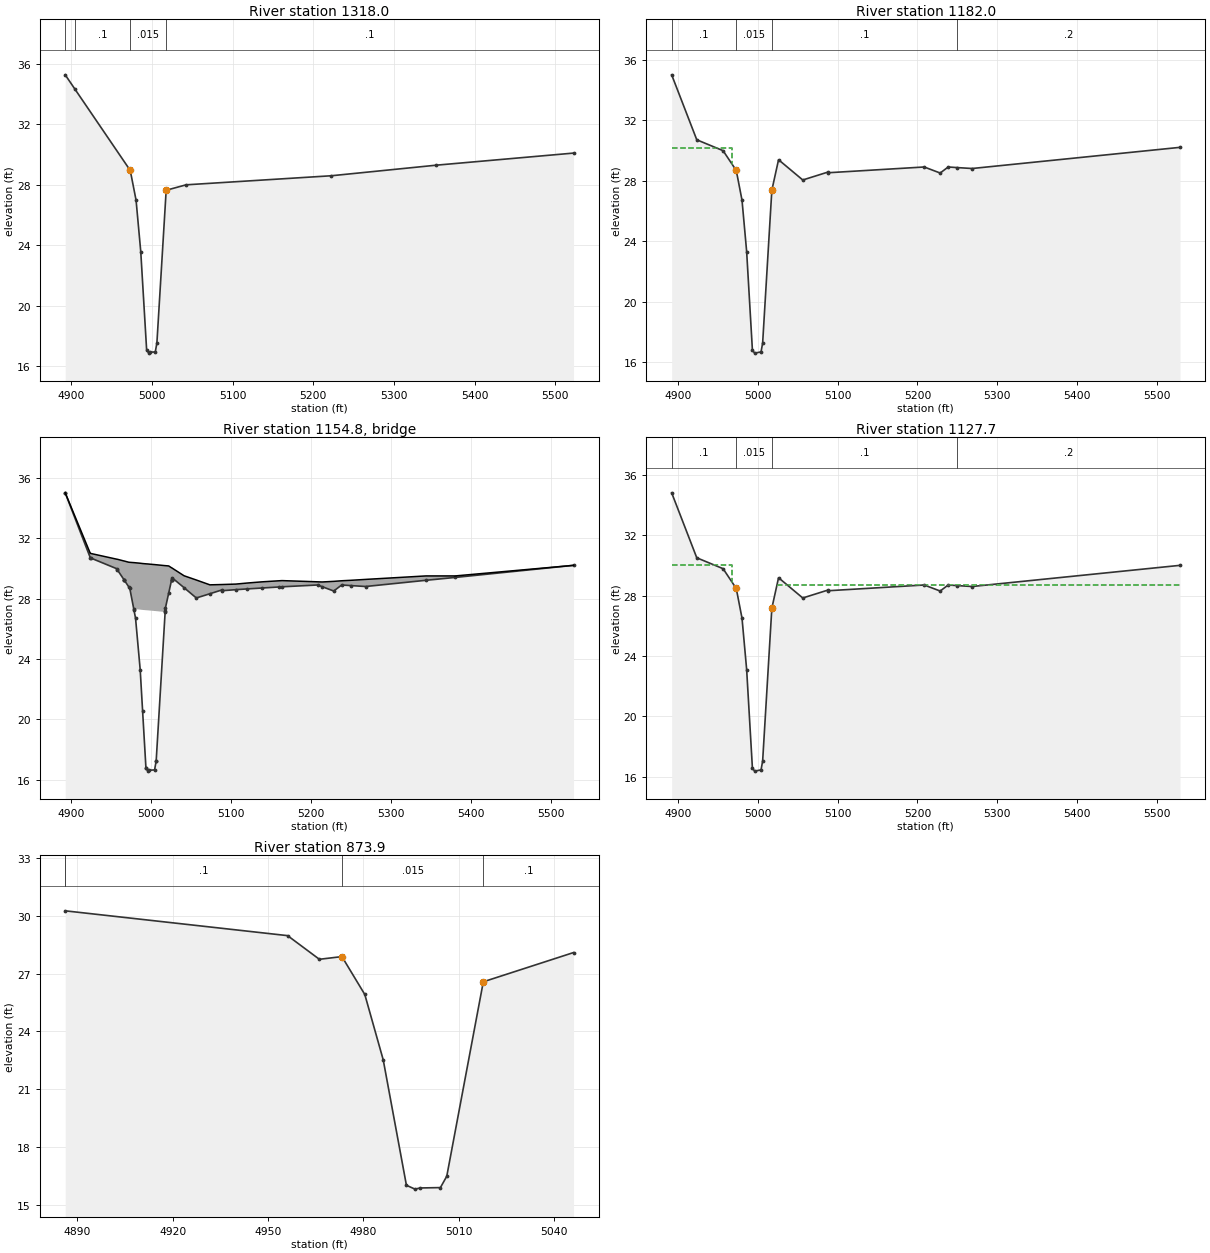
Type RM Length L Ch R = 1 ,1318.0  ,140.2,136.05,133.5
BEGIN DESCRIPTION:
Cross Section 1318.0-Interpolated
END DESCRIPTION:
XS GIS Cut Line= 4
       3166165.4     13805347.42      3166223.33     13805405.34
      3166269.66     13805454.99      3166607.77     13805795.66
#Sta/Elev= 15
  4892.7   35.28  4904.4   34.36  4973.3   28.95  4980.5   26.98  4986.3   23.58
  4993.6   17.06  4996.3   16.86  4997.9   16.92  5004.3   16.94  5006.3   17.53
  5017.8   27.64  5042.5      28  5222.5    28.6  5352.5    29.3  5522.5    30.1
#Mann= 4 , 1 , 0
  4892.7      .2       0  4904.4      .1       0  4973.3    .015       0
  5017.8      .1       0
Bank Sta=4973.3,5017.8
XS Rating Curve= 0 ,0
Exp/Cntr=0.5,0.3

Type RM Length L Ch R = 1 ,1182.0  ,54.3,54.3,54.3
BEGIN DESCRIPTION:
Upstream Section of Bridge/Culvert/Weir
END DESCRIPTION:
XS GIS Cut Line= 5
      3166071.06     13805452.03       3166152.1     13805521.49
      3166205.25     13805569.94      3166310.68     13805666.06
      3166534.94     13805886.67
#Sta/Elev= 21
  4892.5   35.02  4923.9   30.72  4956.8      30  4973.3   28.69  4980.5   26.72
  4986.3   23.32  4993.5    16.8  4996.3    16.6  5004.3   16.68  5006.3   17.27
  5017.8   27.38  5026.2    29.4  5056.5   28.06  5088.4   28.59  5088.5   28.54
  5208.4   28.92  5228.4   28.52  5238.4   28.92  5249.7   28.88  5268.4   28.82
  5528.4   30.22
#Mann= 4 , 1 , 0
  4892.5      .1       0  4973.3    .015       0  5017.8      .1       0
  5249.7      .2       0
#XS Ineff= 2 , 0
       0  4968.4    30.2  5024.2       0    28.9
Permanent Ineff=
       F       F
Bank Sta=4973.3,5017.8
XS Rating Curve= 0 ,0
Exp/Cntr=0.5,0.3

Type RM Length L Ch R = 3 ,1154.8  ,,,
BEGIN DESCRIPTION:
NEVADA AVENUE
Structure ID: C68-1
END DESCRIPTION:
Bridge Culvert--1,0,-1,-1, 0
Deck Dist Width WeirC Skew NumUp NumDn MinLoCord MaxHiCord MaxSubmerge Is_Ogee
10,34.3,2.6,0, 50, 50, , , 0.95, 0, 1,1,,
  4892.5  4892.7  4923.9  4924.2  4956.8  4957.9 4965.89    4966 4966.11  4971.7
  4973.3 4978.31  4978.4  4980.5  4986.3  4989.3  4993.5  4993.6  4996.3  4997.9
  5004.3  5006.2  5006.3 5017.49  5017.6  5017.8    5022 5025.49  5025.6 5025.71
  5026.2  5041.2  5056.5  5073.5  5088.4  5088.5    5106  5120.3    5139  5160.5
  5163.7  5208.4  5213.8  5228.4  5238.4  5249.7  5268.4  5343.8  5380.4  5528.4
      35   34.98   30.99   30.99   30.61    30.6   30.49   30.49   30.49   30.41
    30.4   30.38   30.38   30.37   30.34   30.32    30.3    30.3   30.29   30.28
   30.25   30.24   30.24   30.18   30.18   30.18   30.16   30.04   30.04   30.04
   30.02   29.51   29.23   28.91   28.93   28.93   28.96   29.03   29.11   29.18
   29.19   29.11    29.1   29.14   29.18   29.21   29.27    29.5    29.5    30.2
      35   34.97    30.7   30.69   29.98   29.89   29.26   29.25   29.24    28.8
   28.67    27.3   27.31    27.3   27.27   27.25   27.23   27.23   27.22   27.21
   27.18   27.17   27.17   27.11   27.18   27.36   28.37   29.21   29.24   29.26
   29.38   28.72   28.04   28.32   28.57   28.52   28.59   28.64    28.7   28.77
   28.78    28.9   28.79    28.5    28.9   28.86    28.8   29.21    29.4    30.2
  4892.5  4892.7  4923.9  4924.2  4956.8  4957.9 4965.89    4966 4966.11  4971.7
  4973.3 4978.31  4978.4  4980.5  4986.3  4989.3  4993.5  4993.6  4996.3  4997.9
  5004.3  5006.2  5006.3 5017.49  5017.6  5017.8    5022 5025.49  5025.6 5025.71
  5026.2  5041.2  5056.5  5073.5  5088.4  5088.5    5106  5120.3    5139  5160.5
  5163.7  5208.4  5213.8  5228.4  5238.4  5249.7  5268.4  5343.8  5380.4  5528.4
      35   34.98   30.99   30.99   30.61    30.6   30.49   30.49   30.49   30.41
    30.4   30.38   30.38   30.37   30.34   30.32    30.3    30.3   30.29   30.28
   30.25   30.24   30.24   30.18   30.18   30.18   30.16   30.04   30.04   30.04
   30.02   29.51   29.23   28.91   28.93   28.93   28.96   29.03   29.11   29.18
   29.19   29.11    29.1   29.14   29.18   29.21   29.27    29.5    29.5    30.2
   34.82   34.79   30.52   30.51    29.8   29.71   29.08   29.07   29.06   28.62
   28.49   27.12   27.13   27.12   27.09   27.07   27.05   27.05   27.04   27.03
      27   26.99   26.99   26.93      27   27.18   28.19   29.03   29.06   29.08
    29.2   28.54   27.86   28.14   28.39   28.34   28.41   28.46   28.52   28.59
    28.6   28.72   28.61   28.32   28.72   28.68   28.62   29.03   29.22   30.02
Abutment Skew #Up #Dn= , 2 , 2
  4978.2  4993.6
   27.31   16.77
  4978.2  4993.6
   27.13   16.59
Abutment Skew #Up #Dn= , 2 , 2
  5006.3 5017.69
   17.25   27.11
  5006.3 5017.69
   17.07   26.93
BR Coef= 1 , 1 , 0 ,1.25, 0 ,,,0.8,0,2,0,
WSPro=,,,, 1 ,,,, 0 ,,,, 0 ,,,,-1 ,-1 ,-1 , 0 , 0 , 0 , 0 , 0
BR U #Sta/Elev= 50
  4892.5      35  4892.7   34.97  4923.9    30.7  4924.2   30.69  4956.8   29.98
  4957.9   29.89 4965.89   29.26    4966   29.25 4966.11   29.24  4971.7    28.8
  4973.3   28.67 4978.31    27.3  4978.4   27.27  4980.5    26.7  4986.3    23.3
  4989.3   20.58  4993.5   16.78  4993.6   16.77  4996.3   16.58  4997.9   16.64
  5004.3   16.66  5006.2   17.22  5006.3   17.25 5017.49   27.09  5017.6   27.18
  5017.8   27.36    5022   28.37 5025.49   29.21  5025.6   29.24 5025.71   29.26
  5026.2   29.38  5041.2   28.72  5056.5   28.04  5073.5   28.32  5088.4   28.57
  5088.5   28.52    5106   28.59  5120.3   28.64    5139    28.7  5160.5   28.77
  5163.7   28.78  5208.4    28.9  5213.8   28.79  5228.4    28.5  5238.4    28.9
  5249.7   28.86  5268.4    28.8  5343.8   29.21  5380.4    29.4  5528.4    30.2
BR U #Mann= 4
  4892.5      .1  4973.3    .015  5017.8      .1  5249.7      .2
BR U Banks=4973.3,5017.8
BR D #Sta/Elev= 50
  4892.5   34.82  4892.7   34.79  4923.9   30.52  4924.2   30.51  4956.8    29.8
  4957.9   29.71 4965.89   29.08    4966   29.07 4966.11   29.06  4971.7   28.62
  4973.3   28.49 4978.31   27.12  4978.4   27.09  4980.5   26.52  4986.3   23.12
  4989.3    20.4  4993.5    16.6  4993.6   16.59  4996.3    16.4  4997.9   16.46
  5004.3   16.48  5006.2   17.04  5006.3   17.07 5017.49   26.91  5017.6      27
  5017.8   27.18    5022   28.19 5025.49   29.03  5025.6   29.06 5025.71   29.08
  5026.2    29.2  5041.2   28.54  5056.5   27.86  5073.5   28.14  5088.4   28.39
  5088.5   28.34    5106   28.41  5120.3   28.46    5139   28.52  5160.5   28.59
  5163.7    28.6  5208.4   28.72  5213.8   28.61  5228.4   28.32  5238.4   28.72
  5249.7   28.68  5268.4   28.62  5343.8   29.03  5380.4   29.22  5528.4   30.02
BR D #Mann= 4
  4892.5      .1  4973.3    .015  5017.8      .1  5249.7      .2
BR D Banks=4973.3,5017.8
BC Design=,, 0 ,, 0 ,,,,,,
BC HTab HWMax=35.02
BC Use User HTab Curves=0
BC User HTab FreeFlow(D)= 0

Type RM Length L Ch R = 1 ,1127.7  ,253.75,253.75,253.75
BEGIN DESCRIPTION:
Downstream Section of Bridge/Culvert/Weir
END DESCRIPTION:
XS GIS Cut Line= 5
      3166035.67     13805493.21       3166116.7     13805562.67
      3166169.85     13805611.12      3166275.28     13805707.24
      3166499.55     13805927.84
#Sta/Elev= 21
  4892.5    34.8  4923.9    30.5  4956.8   29.78  4973.3   28.47  4980.5    26.5
  4986.3    23.1  4993.5   16.58  4996.3   16.38  5004.3   16.46  5006.3   17.05
  5017.8   27.16  5026.2   29.18  5056.5   27.84  5088.4   28.37  5088.5   28.32
  5208.4    28.7  5228.4    28.3  5238.4    28.7  5249.7   28.66  5268.4    28.6
  5528.4      30
#Mann= 4 , 1 , 0
  4892.5      .1       0  4973.3    .015       0  5017.8      .1       0
  5249.7      .2       0
#XS Ineff= 2 , 0
       0  4968.4      30  5024.2       0    28.7
Permanent Ineff=
       F       F
Bank Sta=4973.3,5017.8
XS Rating Curve= 0 ,0
Exp/Cntr=0.5,0.3

Type RM Length L Ch R = 1 ,873.9   ,0,0,0
BEGIN DESCRIPTION:
Cross Section 873.9-Interpolated
END DESCRIPTION:
XS GIS Cut Line= 2
      3165860.08     13805687.95      3165985.18     13805787.68
#Sta/Elev= 13
  4886.2   30.27  4956.2   28.98  4966.2   27.75  4973.3   27.89  4980.5   25.92
  4986.3   22.52  4993.6      16  4996.3    15.8  4997.9   15.86  5004.3   15.88
  5006.3   16.47  5017.8   26.58  5046.2    28.1
#Mann= 4 , 1 , 0
  4886.2      .2       0  4886.2      .1       0  4973.3    .015       0
  5017.8      .1       0
Bank Sta=4973.3,5017.8
XS Rating Curve= 0 ,0
Exp/Cntr=0.3,0.1
Stream Node=C106-08-00      ,C106-08-00_0009 , 0 , 0 ,Upstream end
Stream Node=C106-08-00      ,C106-08-00_0009 , 0 , 1 ,Downstream end

Chan Stop Cuts=-1
Use User Specified Reach Order=0
Composite Channel Slope=5